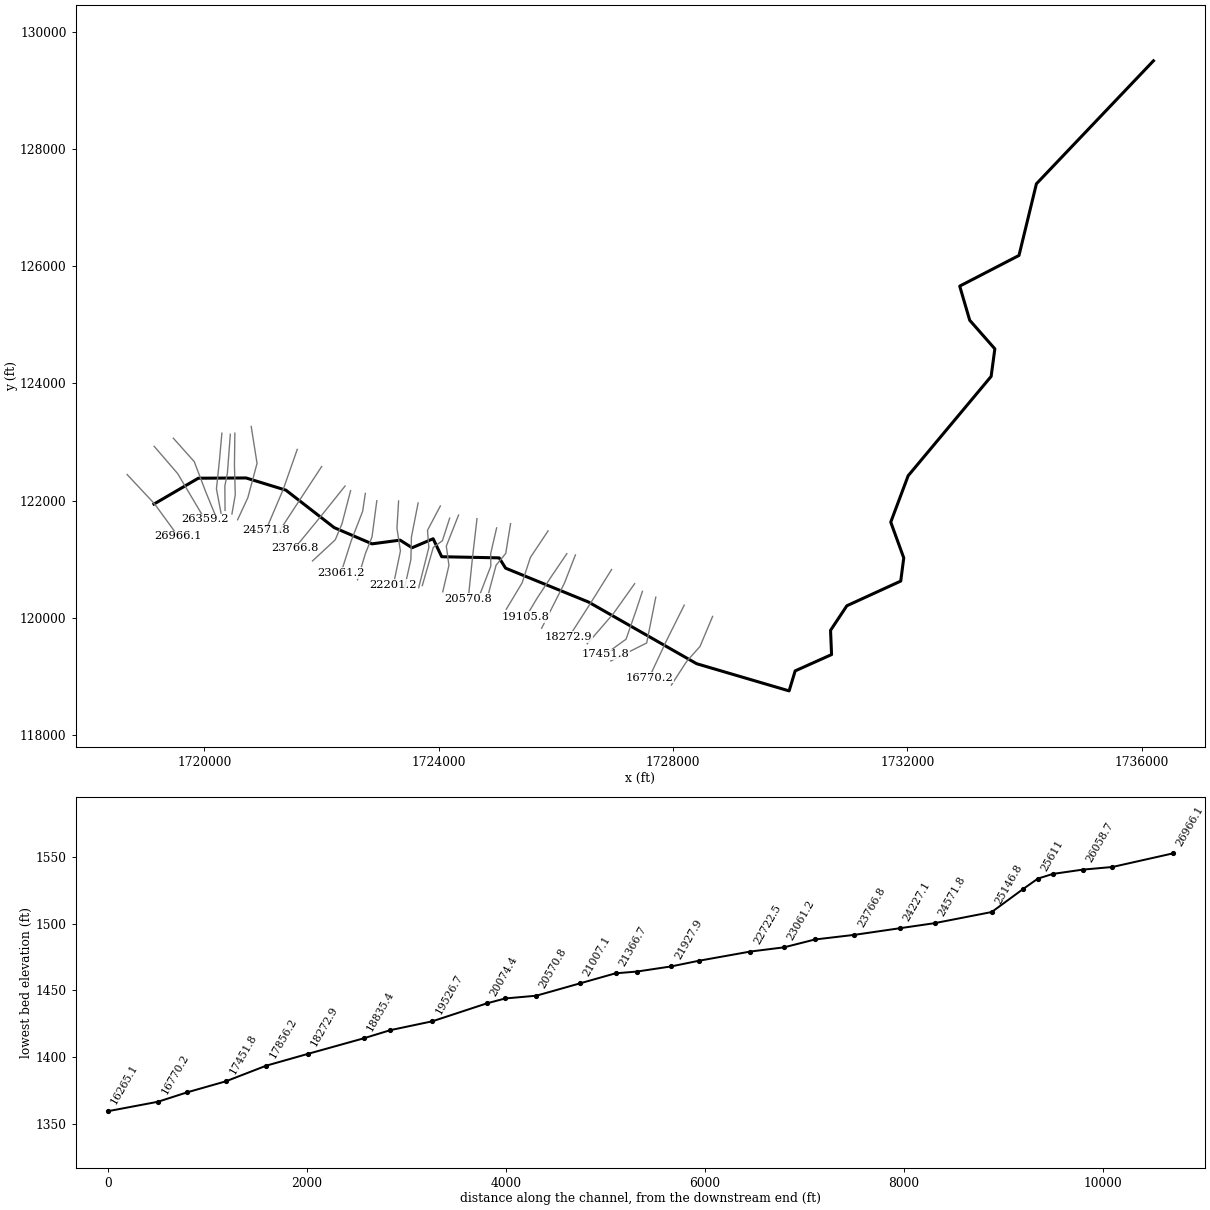
--- Bradshaw Creek.prj (project) ---

Proj Title=Bradshaw Creek
Current Plan=p01
Default Exp/Contr=0,0
English Units
Geom File=g01
Flow File=f01
Plan File=p01
BEGIN DESCRIPTION:
END DESCRIPTION:
DSS Export Rating Curves= 0
DSS Export Rating Curve Sorted= 0
DSS Export Volume Flow Curves= 0
DXF OffsetX= 0
DXF OffsetY= 0
DXF ScaleX= 0
DXF ScaleY= 0

--- Bradshaw Creek.p01 (plan) ---

Plan Title=Floodplain
Program Version=4.00
Geom File=g01
Flow File=f01
K Sum by GR=0
Std Step Tol=0.01
Critical Tol=0.01
Num of Std Step Trials=20
Max Error Tol=0.3
Flow Tol Ratio=0.001
Split Flow NTrial=30
Split Flow Tol=0.02
Split Flow Ratio=0.02
Log Output Level=0
Friction Slope Method=1
Unsteady Friction Slope Method=2
Unsteady Bridges Friction Slope Method=1
Global Log Level=0
CheckData=False
Run HTab=0
Run UNet=0
Run PostProcess=0
UNET Theta=0
UNET Theta Warmup=0
UNET ZTol=0
UNET ZSATol=0
UNET MxIter=0
UNET MaxInSteps=0
UNET DtIC=0
UNET DtMin=0
UNET MaxCRTS=0
UNET WFStab=0
UNET SFStab=0
UNET WFX=0
UNET SFX=0
UNET DSS MLevel=0
UNET DZMax Abort=0
UNET Convert EG Bridges=0
UNET Use Existing IB Tables=0
UNET Froude Limit=0
UNET Froude Power=0
Write IC File=0
Echo Input=False
Echo Output=False
Write Detailed=0

--- Bradshaw Creek.f01 (steady flow) ---

Flow Title=NFF Regression Equation
Program Version=4.00
Number of Profiles=1
Profile Names=P100yr
River Rch & RM=Bradshaw Creek,Main      ,26966.1
657.4505
River Rch & RM=Bradshaw Creek,Main      ,26359.2
667.7370
River Rch & RM=Bradshaw Creek,Main      ,26058.7
850.1257
River Rch & RM=Bradshaw Creek,Main      ,23370.2
942.2427
River Rch & RM=Bradshaw Creek,Main      ,23061.2
1079.424
River Rch & RM=Bradshaw Creek,Main      ,20257.9
1150.306
River Rch & RM=Bradshaw Creek,Main      ,17061.7
1276.547
River Rch & RM=Bradshaw Creek,Main      ,16770.2
1657.952
River Rch & RM=Bradshaw Creek,Main      ,14372.1
1706.803
River Rch & RM=Bradshaw Creek,Main      ,14066.5
3537.598
River Rch & RM=Bradshaw Creek,Main      ,8942.8
3818.219
Boundary for River Rch & Prof#=Bradshaw Creek,Main      ,1
Up Type=0
Dn Type=3
Dn Slope=0.011731

--- Bradshaw Creek.g01 (geometry) ---

Geom Title=USGS 10m DEM
Program Version=4.00

River Reach=Bradshaw Creek  ,Main
Reach XY= 30
     1719140.251      121943.533     1719898.019      122384.474
     1720712.862      122388.748     1721392.201      122180.686
     1722216.907      121541.459     1722863.264      121264.921
     1723341.319      121328.266       1723546.2      121198.607
     1723905.484       121352.02     1724051.969      121045.193
      1725032.94      121025.885     1725141.893      120850.395
     1726557.362      120272.751      1728402.89      119220.715
     1729981.637      118756.862     1730084.895      119098.141
     1730706.164      119376.286     1730688.727      119789.771
     1730967.154      120208.882     1731886.892      120629.918
     1731938.401      121025.343     1731716.409      121635.165
     1732013.645      122426.688      1733429.92      124120.925
     1733493.277      124590.993     1733064.085      125078.773
     1732893.625      125660.603     1733905.438      126183.772
     1734202.579      127405.758     1736200.601      129503.468

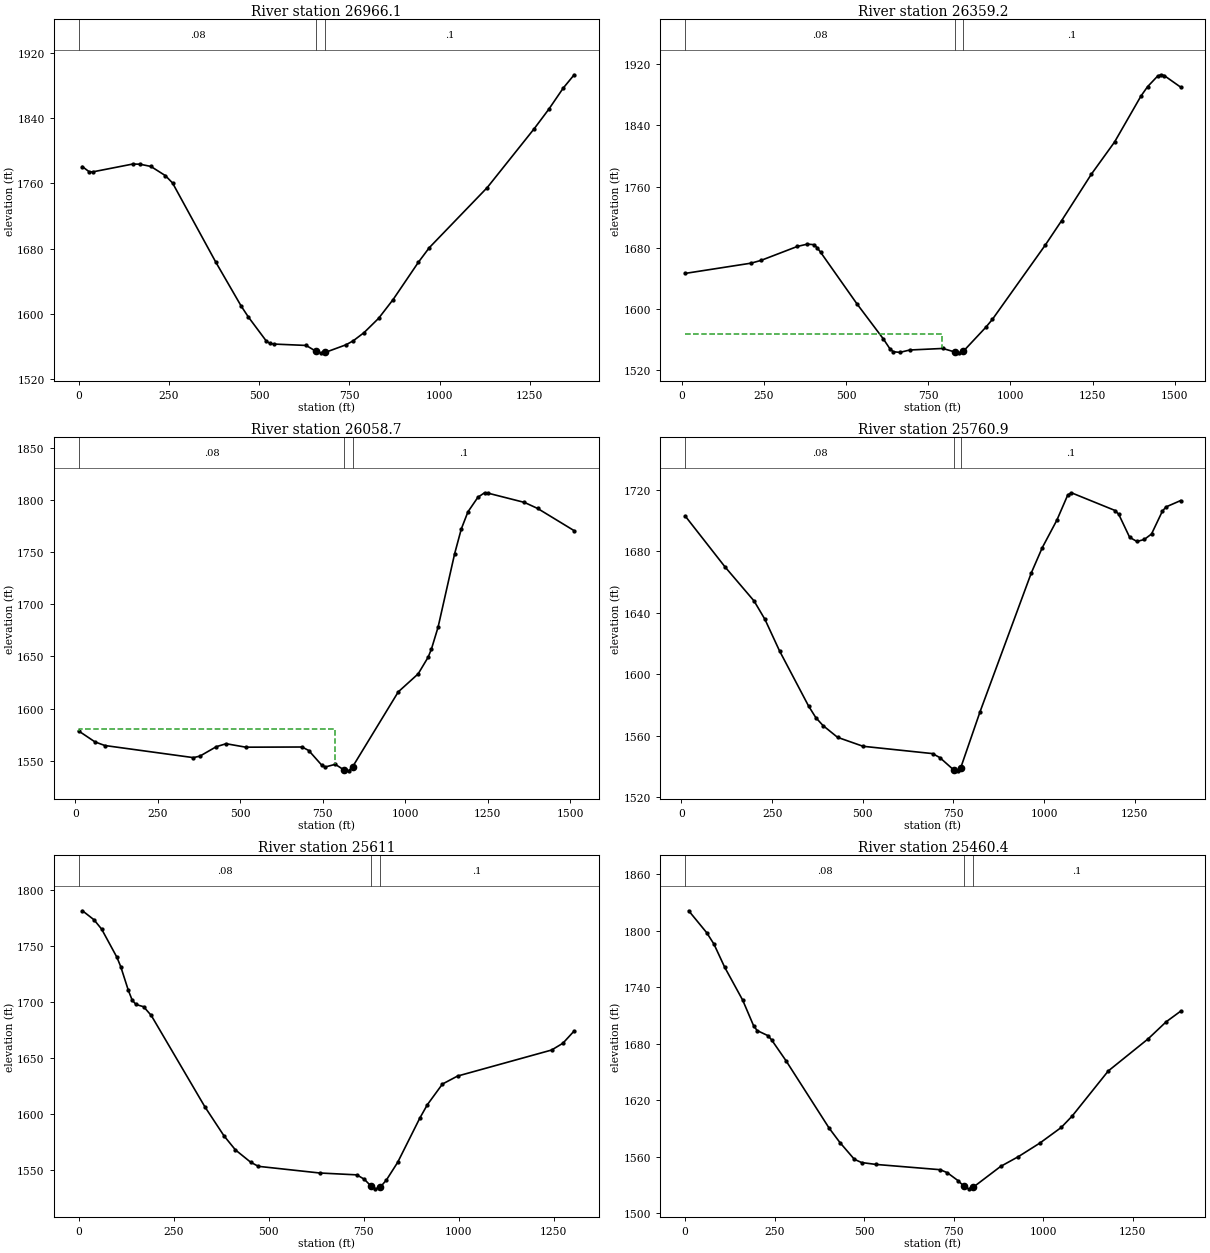
Type RM Length L Ch R = 1 ,26966.1 ,612.9,606.9,604.2
XS GIS Cut Line= 3
     1718682.079      122447.339     1719147.322      121950.604
     1719556.021       121391.61
#Sta/Elev= 30
      10 1780.63      30 1773.99      40 1774.16   150.1 1783.69   170.1 1783.48
   200.2 1780.74   240.2 1769.54   260.2 1760.52   380.3 1663.35   450.4 1609.75
   470.4 1596.32   520.4  1566.7   530.5 1563.97   540.5 1563.24   630.5 1561.53
   658.1 1554.24   670.6 1552.48   683.1 1552.97   740.8 1562.32   760.9 1567.22
     791 1577.29   831.1 1594.69   871.3 1617.69   941.5 1663.46   971.6 1681.23
  1132.2 1754.87  1262.7 1827.16  1302.8  1850.8  1342.9 1876.78  1373.1 1892.99
#Mann= 3 , 0 , 0
       0     .08       0   658.1    .045       0   683.1      .1       0
Bank Sta=658.1,683.1
XS Rating Curve= 0 ,0
Exp/Cntr=0.3,0.1

Type RM Length L Ch R = 1 ,26359.2 ,305.2,300.5,295.7
XS GIS Cut Line= 3
      1719144.43      122928.001     1719544.628      122463.485
     1720006.978      121686.092
#Sta/Elev= 30
    10.1 1646.28   211.1 1659.72   241.2 1663.34   351.8 1681.62     382 1684.61
   402.1 1683.91   412.1 1679.82   422.2 1674.05   532.7 1606.56   613.1 1560.59
   633.2 1547.62   643.3  1543.8   663.4 1542.92   693.5 1546.02     794 1548.06
   831.8 1543.28   844.3 1542.32   856.8 1544.49   924.7 1575.67   944.8 1586.04
  1105.6 1683.24  1155.8 1715.53  1246.3 1776.34  1316.6 1818.28    1397 1878.51
  1417.1 1890.76  1447.3 1904.43  1457.3 1906.28  1467.4 1905.33  1517.6 1890.11
#Mann= 3 , 0 , 0
    10.1     .08       0   831.8    .045       0   856.8      .1       0
#XS Ineff= 2 , 0
          792.22 1566.79
Permanent Ineff=
       F       F
Bank Sta=831.8,856.8
XS Rating Curve= 0 ,0
Exp/Cntr=0.3,0.1

Type RM Length L Ch R = 1 ,26058.7 ,310.7,297.8,284.8
XS GIS Cut Line= 4
     1719470.715       123067.11     1719828.034      122666.912
     1720020.987      122159.519     1720185.354      121759.321
#Sta/Elev= 30
     9.9 1578.55    59.6 1568.03    89.4 1564.59   357.7 1552.98   377.5 1554.42
   427.2 1563.46     457 1566.31   516.6 1562.99   687.3 1563.16   707.4 1559.81
   747.6 1545.48   757.7 1544.03   787.8 1546.57   815.5 1540.91     828 1540.32
   840.5 1544.25   978.8 1616.02  1039.1 1633.26  1069.3 1649.22  1079.3 1657.04
  1099.5 1678.07  1149.8 1748.58  1169.9 1772.19    1190 1788.57  1220.2 1802.54
  1240.3 1806.83  1250.4  1806.5  1361.1 1797.61  1401.3  1791.8    1512  1770.5
#Mann= 3 , 0 , 0
     9.9     .08       0   815.5    .045       0   840.5      .1       0
#XS Ineff= 2 , 0
          785.84 1580.71
Permanent Ineff=
       F       F
Bank Sta=815.5,840.5
XS Rating Curve= 0 ,0
Exp/Cntr=0.3,0.1

Type RM Length L Ch R = 1 ,25760.9 ,152.4,149.9,147.5
XS GIS Cut Line= 4
     1720299.696      123152.867     1720256.818      122674.059
     1720206.793      122202.397     1720285.404      121787.906
#Sta/Elev= 30
      10 1703.08   120.2 1669.85   200.3 1647.68   230.3  1635.7   270.4 1615.25
   350.5 1579.36   370.6 1571.75   390.6 1566.57   430.6 1558.94   500.9 1553.11
   692.6 1548.35   712.8 1545.73   750.8 1537.74   763.3 1537.13  770.53 1539.28
   823.8 1575.73   965.1 1666.04   995.2 1682.39  1035.4 1700.25  1065.5 1716.67
  1075.6 1718.12  1196.1 1706.58  1206.2 1704.08  1236.3 1689.11  1256.4 1686.42
  1276.5 1687.71  1296.6  1691.3  1326.7 1706.22  1336.7 1708.93  1376.9 1713.05
#Mann= 3 , 0 , 0
      10     .08       0   750.8    .045       0  770.53      .1       0
Bank Sta=750.8,770.53
XS Rating Curve= 0 ,0
Exp/Cntr=0.3,0.1

Type RM Length L Ch R = 1 ,25611   ,144.5,150.6,156.8
XS GIS Cut Line= 4
     1720443.783      123133.273     1720393.859       122470.95
     1720350.591      122251.285      1720353.92      121835.253
#Sta/Elev= 30
    10.1 1781.44    40.3 1773.46    60.4 1765.18   100.6 1740.09   110.7 1731.77
   130.8 1710.54   140.9 1701.86     151 1697.94   171.1 1695.92   191.2 1688.12
   332.1 1606.82   382.4 1580.95   412.6 1568.35   452.9 1557.34     473 1553.71
     634 1547.78   732.3  1546.1   751.8 1542.19   768.5 1536.44     781 1533.65
   793.5 1535.03   810.2 1541.65   839.4 1557.13     898 1596.75   917.8 1608.66
   957.4 1627.03   997.1 1634.14  1244.7 1657.35  1274.4  1663.4  1304.1 1674.34
#Mann= 3 , 0 , 0
       0     .08       0   768.5    .045       0   793.5      .1       0
Bank Sta=768.5,793.5
XS Rating Curve= 0 ,0
Exp/Cntr=0.3,0.1

Type RM Length L Ch R = 1 ,25460.4 ,322,313.5,305.1
XS GIS Cut Line= 4
     1720521.234      123152.867     1720514.088      122609.741
     1720528.381      122102.348      1720471.21      121773.613
#Sta/Elev= 30
    10.1 1821.19    60.4 1797.89    80.5 1785.87   110.6  1761.2   160.9 1726.24
   191.1 1699.28   201.2 1693.94   231.4 1688.52   241.4 1684.17   281.6 1662.06
   402.4 1590.25   432.5 1574.97   472.8 1557.15   492.9 1553.71   533.1 1551.69
   712.4 1546.09   732.3 1542.95   762.1 1534.59   779.5 1528.37     792 1525.75
   804.5 1527.35   881.6 1549.59   931.3 1560.01   991.1 1574.37  1050.8 1590.95
  1081.1 1602.97  1182.2 1650.99  1293.4 1685.05    1344 1703.23  1384.4  1714.5
#Mann= 3 , 0 , 0
       0     .08       0   779.5    .045       0   804.5      .1       0
Bank Sta=779.5,804.5
XS Rating Curve= 0 ,0
Exp/Cntr=0.3,0.1

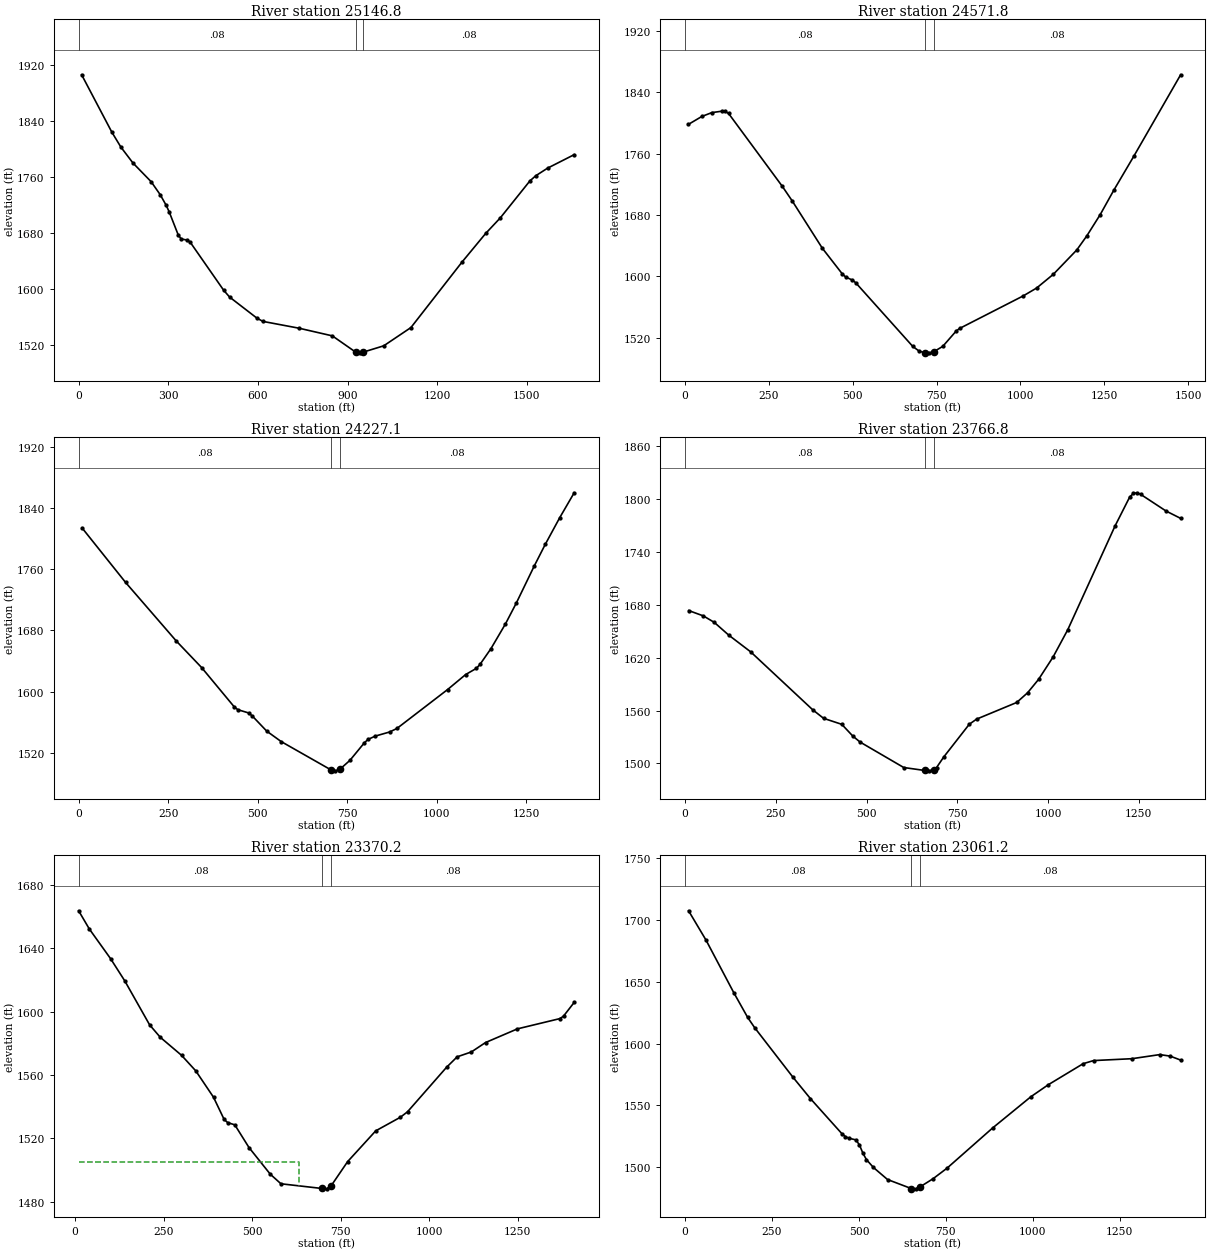
Type RM Length L Ch R = 1 ,25146.8 ,577.6,575,570.1
XS GIS Cut Line= 4
     1720799.944      123267.209     1720899.993      122638.327
     1720742.773      122052.323     1720568.108      121675.999
#Sta/Elev= 30
    10.1 1906.44   111.2  1824.3   141.5 1802.92   181.9 1780.18   242.6 1753.52
   272.9 1734.95   293.1 1719.62   303.2 1710.18   333.6 1676.98   343.7 1671.39
   363.9 1669.98     374 1666.54   485.2 1598.27   505.4 1588.35   596.4 1558.36
   616.6 1553.61   737.9 1543.83   849.1  1532.9   927.7 1509.47   940.2 1508.62
   952.7 1509.68  1021.1 1518.67  1112.1 1544.81    1283 1638.46  1362.1 1679.38
  1411.4 1701.82  1510.2  1754.6    1530 1762.03  1569.5 1772.88  1658.4 1792.15
#Mann= 3 , 0 , 0
       0     .08       0   927.7    .045       0   952.7     .08       0
Bank Sta=927.7,952.7
XS Rating Curve= 0 ,0
Exp/Cntr=0.3,0.1

Type RM Length L Ch R = 1 ,24571.8 ,351.1,344.8,340.7
XS GIS Cut Line= 3
     1721586.476      122876.445     1721344.915      122189.138
     1721051.354      121499.764
#Sta/Elev= 30
      10 1798.27    49.9 1808.58    79.8 1813.61   109.8 1815.45   119.8 1815.13
   129.7 1812.47   289.4 1717.74   319.4 1698.46   409.2 1636.74     469  1603.1
     479 1599.11     499 1595.14     509  1591.6   678.6 1508.81   698.6 1502.29
     716 1500.47   728.5 1500.27     741 1501.57   768.5 1508.75   808.4  1528.7
   818.4 1532.04  1008.3 1574.52  1048.2 1584.76  1098.2 1602.73  1168.1 1634.46
  1198.1 1652.87    1238  1680.6    1278 1712.03  1337.9 1756.52  1477.8 1862.94
#Mann= 3 , 0 , 0
       0     .08       0     716    .045       0     741     .08       0
Bank Sta=716,741
XS Rating Curve= 0 ,0
Exp/Cntr=0.3,0.1

Type RM Length L Ch R = 1 ,24227.1 ,462.9,460.3,457.4
XS GIS Cut Line= 2
     1722002.681      122583.728     1721243.449      121426.585
#Sta/Elev= 30
    10.1  1813.5   131.3 1742.53   272.8 1666.08   343.5 1631.43   434.4 1580.19
   444.5 1576.43   474.8 1572.15   484.9 1568.24   525.3 1548.42   565.7 1534.77
   704.7  1497.8   717.2 1496.53   729.7 1498.59   757.7 1510.22   798.1  1533.2
   808.2 1537.55   828.4  1541.9   868.8 1547.31     889 1551.89  1030.4 1602.68
  1080.9  1622.3  1111.2 1630.48  1121.3 1635.76  1151.6 1656.15    1192 1688.36
  1222.4 1715.69  1272.9 1764.47  1303.2 1792.29  1343.6 1827.15    1384 1859.71
#Mann= 3 , 0 , 0
       0     .08       0   704.7    .045       0   729.7     .08       0
Bank Sta=704.7,729.7
XS Rating Curve= 0 ,0
Exp/Cntr=0.3,0.1

Type RM Length L Ch R = 1 ,23766.8 ,388.9,396.6,404.6
XS GIS Cut Line= 3
     1722402.471      122251.202       1721975.7      121718.518
     1721542.559      121191.089
#Sta/Elev= 30
      10 1673.56    50.2 1667.53    80.3 1660.18   120.5 1645.58   180.7 1626.66
   351.3 1560.96   381.4 1551.19   431.6 1544.35   461.7 1531.14   481.8 1524.27
   602.3  1495.3     660 1491.95   672.5 1491.53     685 1492.94   692.6 1495.24
   712.7 1507.41   782.9 1544.49     803 1550.27   913.4 1569.17   943.5 1580.23
   973.6 1595.37  1013.8 1620.96  1053.9 1651.66  1184.4 1769.73  1224.5  1802.4
  1234.6  1806.6  1244.6 1807.36  1254.6 1805.65  1324.9 1786.61    1365 1778.29
#Mann= 3 , 0 , 0
       0     .08       0     660    .045       0     685     .08       0
Bank Sta=660,685
XS Rating Curve= 0 ,0
Exp/Cntr=0.3,0.1

Type RM Length L Ch R = 1 ,23370.2 ,306.3,309,311.7
XS GIS Cut Line= 4
      1722496.64      122172.096     1722350.282      121609.532
      1722235.94      121335.111     1721847.176      120973.789
#Sta/Elev= 30
      10 1663.59    40.1 1652.13   100.2 1633.37   140.3 1619.34   210.5 1591.56
   240.5 1583.74   300.7 1572.33   340.8 1562.53   390.9 1545.88   420.9 1531.85
     431 1529.86     451 1528.46   491.1 1514.12   551.2  1497.3   581.3 1491.25
   697.6 1488.28   710.1 1488.06   722.6 1489.83   769.6 1505.25   848.9 1524.66
   918.6 1533.26   938.7  1536.7  1048.8 1564.76  1078.9  1571.4  1118.9 1574.46
    1159 1580.41  1249.1 1589.05  1369.3 1595.54  1379.3 1597.11  1409.3 1605.74
#Mann= 3 , 0 , 0
      10     .08       0   697.6    .045       0   722.6     .08       0
#XS Ineff= 2 , 0
          631.66 1504.84
Permanent Ineff=
       F       F
Bank Sta=697.6,722.6
XS Rating Curve= 0 ,0
Exp/Cntr=0.3,0.1

Type RM Length L Ch R = 1 ,23061.2 ,338.6,338.6,338.6
XS GIS Cut Line= 4
     1722748.193      122126.359     1722702.456      121819.922
     1722505.787      121312.243     1722332.092      120768.528
#Sta/Elev= 30
      10 1707.58      60 1683.89   139.9 1641.25   179.9 1621.16   199.9 1612.88
   309.8 1572.82   360.2 1555.41     451 1526.88   461.1  1524.5   471.1 1523.24
   491.3 1521.89   501.4 1517.77   511.5 1511.01   521.6 1505.86   541.7 1499.51
   582.1 1489.77   650.2 1482.48   662.7 1482.21   675.2 1483.73   713.1  1490.4
   753.5 1499.01   884.3 1531.52   994.5 1556.88  1044.5 1566.59  1144.7 1583.64
  1174.7 1586.17  1284.9 1587.69    1365 1591.01    1395 1589.79  1425.1 1586.56
#Mann= 3 , 0 , 0
       0     .08       0   650.2    .045       0   675.2     .08       0
Bank Sta=650.2,675.2
XS Rating Curve= 0 ,0
Exp/Cntr=0.3,0.1

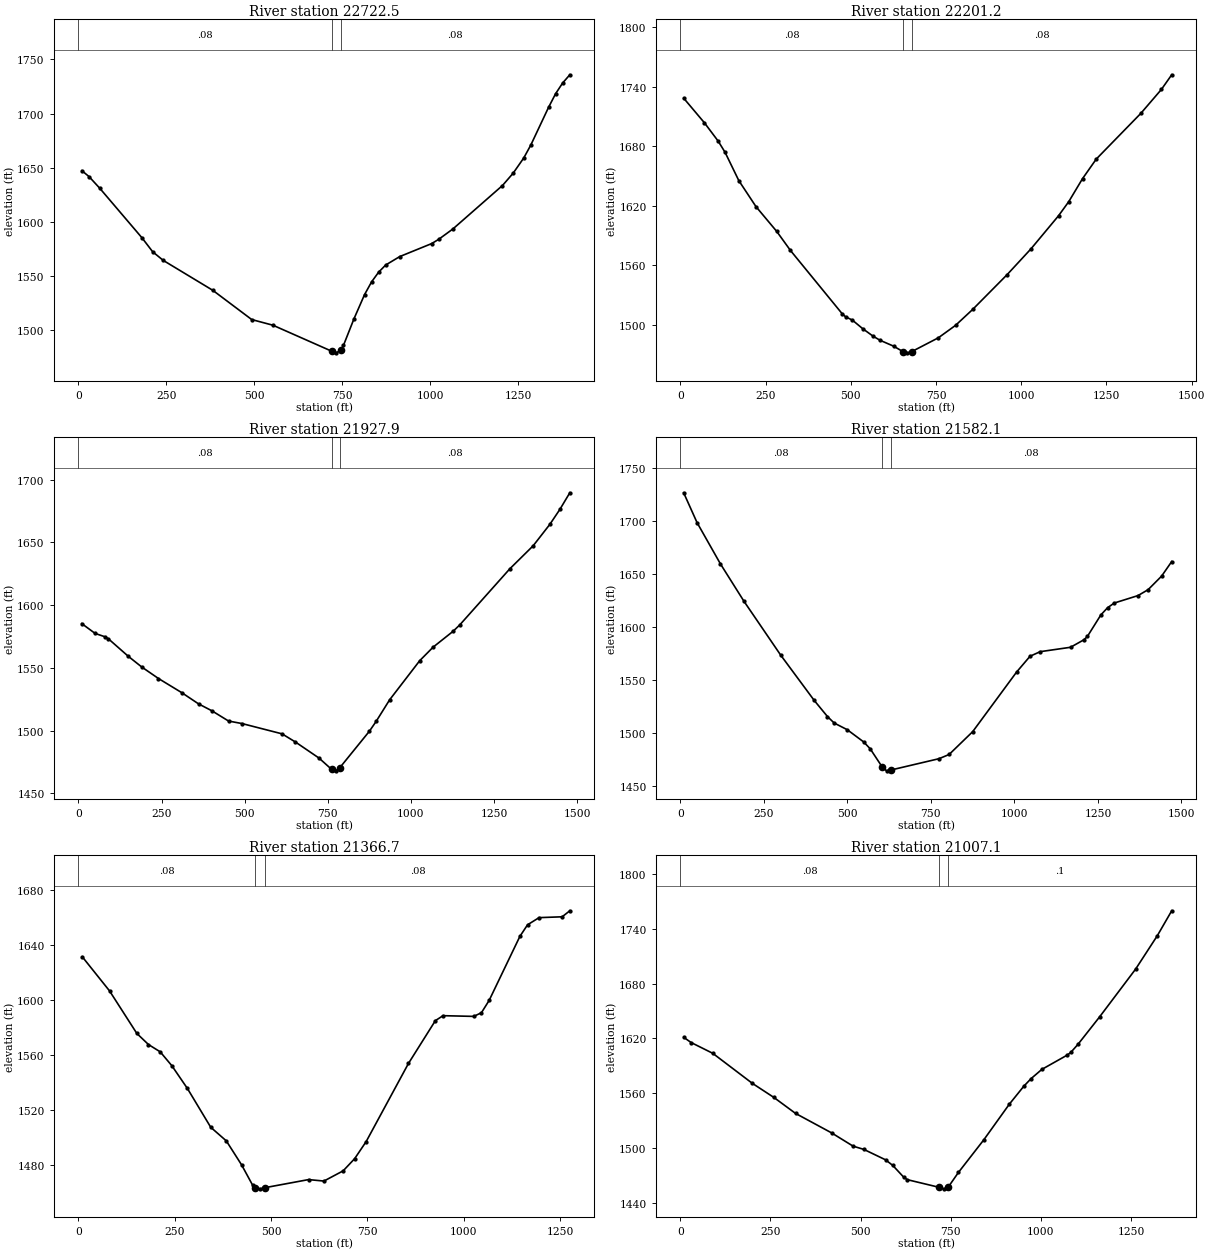
Type RM Length L Ch R = 1 ,22722.5 ,506.6,521.3,536
XS GIS Cut Line= 4
     1722944.307       122000.47     1722861.981      121383.022
     1722747.639       121094.88     1722615.002      120651.232
#Sta/Elev= 30
      10 1647.21    30.1 1641.81    60.3 1631.15   180.8 1585.17     211 1572.36
   241.1 1564.38   381.8 1536.77   492.3 1509.79   552.6 1504.55   720.4 1480.43
   732.9 1479.05   745.4 1481.74   752.9 1485.88   782.9 1510.54   812.9 1532.85
   832.9  1544.6   852.9 1553.56   872.9 1560.15   912.9 1567.95  1003.4 1579.92
  1023.5 1583.87  1063.8 1593.43  1204.7 1633.57  1234.9  1644.9  1265.1 1658.97
  1285.2 1670.93  1335.6 1705.73  1355.7 1718.38  1375.8  1728.3    1396 1735.82
#Mann= 3 , 0 , 0
       0     .08       0   720.4    .045       0   745.4     .08       0
Bank Sta=720.4,745.4
XS Rating Curve= 0 ,0
Exp/Cntr=0.3,0.1

Type RM Length L Ch R = 1 ,22201.2 ,278.6,273.3,268
XS GIS Cut Line= 4
     1723315.941      121995.386     1723287.888       121531.78
     1723347.346      121143.016     1723228.306      120571.499
#Sta/Elev= 30
    10.1 1728.23    70.7 1703.56   111.1  1685.1   131.3 1673.84   171.6 1645.38
   222.1 1619.15   282.7 1594.33   323.1  1575.1   474.5 1511.56   484.6 1508.41
   504.8 1505.01     535 1496.42   565.3 1488.91   585.5 1484.81   625.8  1478.8
   653.6 1473.23   666.1 1472.11   678.6  1473.3   756.9 1487.24   807.3 1499.74
   857.7 1515.81   958.4 1550.69  1028.8  1576.8  1109.4    1610  1139.6  1624.3
  1179.8 1647.35  1220.1 1667.05  1350.9 1713.05  1411.3 1737.17  1441.5 1751.88
#Mann= 3 , 0 , 0
       0     .08       0   653.6    .045       0   678.6     .08       0
Bank Sta=653.6,678.6
XS Rating Curve= 0 ,0
Exp/Cntr=0.3,0.1

Type RM Length L Ch R = 1 ,21927.9 ,341.9,345.9,349.5
XS GIS Cut Line= 4
      1723649.21      121961.707     1723534.868      121380.848
      1723525.72      120996.658     1723415.952      120507.273
#Sta/Elev= 30
      10 1585.26    50.2 1577.43    80.3 1574.72    90.3  1573.1   150.5 1559.08
   190.6 1550.65   240.8  1541.5   311.1 1530.18   361.2 1521.31   401.4 1515.78
   451.5 1507.62   491.7 1505.63   612.2 1497.43   652.7  1490.9   723.5 1478.12
   761.5  1469.1     774 1467.94   786.5 1470.58   875.2 1499.56   895.4 1507.36
   935.9 1524.53  1026.5 1555.75  1066.6 1566.47  1126.8 1579.14  1146.8 1584.21
  1297.3  1628.9  1367.5 1647.25  1417.7 1664.32  1447.8 1676.21  1477.8  1689.5
#Mann= 3 , 0 , 0
       0     .08       0   761.5    .045       0   786.5     .08       0
Bank Sta=761.5,786.5
XS Rating Curve= 0 ,0
Exp/Cntr=0.3,0.1

Type RM Length L Ch R = 1 ,21582.1 ,243.5,215.4,187.2
XS GIS Cut Line= 4
     1724028.826      121911.396     1723809.289       121495.19
     1723832.158      121202.474     1723659.074      120517.187
#Sta/Elev= 30
      10 1726.62    50.1 1698.44   120.1 1659.45   190.2 1624.32   300.4 1573.35
   400.5 1530.67   440.5 1515.31   460.5 1509.22   499.9 1502.86   548.9 1491.34
   568.4 1484.88   604.9 1467.42   617.4 1464.06   629.9  1464.8   774.3 1475.52
   804.6 1479.49   875.2 1501.06  1006.5 1557.29  1046.9 1572.27  1077.2 1576.58
  1168.1 1580.73  1208.4 1587.86  1218.5 1590.94  1258.9 1611.28  1279.1 1618.14
  1299.3 1622.54    1370 1629.53  1400.3 1635.12  1440.7 1647.91    1471 1661.69
#Mann= 3 , 0 , 0
       0     .08       0   604.9    .045       0   629.9     .08       0
Bank Sta=604.9,629.9
XS Rating Curve= 0 ,0
Exp/Cntr=0.3,0.1

Type RM Length L Ch R = 1 ,21366.7 ,328.1,359.7,390.9
XS GIS Cut Line= 4
     1724187.857      121703.401     1724063.874      121318.735
       1723908.1      121204.288     1723720.536      120552.582
#Sta/Elev= 30
    10.1  1631.2    80.8 1606.45   151.6 1575.59   181.9  1567.5   212.2 1562.25
   242.5 1552.15   282.9 1535.62   343.5 1507.44   383.9 1497.57   423.5 1480.18
   452.5 1465.25   459.3  1463.6   471.8 1462.75   484.3  1463.6   597.4 1469.46
   637.3  1468.4   687.2 1475.81   717.1 1484.67     747 1497.09   856.7 1553.77
   926.6 1584.87   946.5 1588.47  1026.3 1587.95  1046.2 1590.63  1066.2 1599.56
    1146 1646.05  1165.9 1654.46  1195.8 1659.65  1255.7 1660.26  1275.6 1664.63
#Mann= 3 , 0 , 0
       0     .08       0   459.3    .045       0   484.3     .08       0
Bank Sta=459.3,484.3
XS Rating Curve= 0 ,0
Exp/Cntr=0.3,0.1

Type RM Length L Ch R = 1 ,21007.1 ,443.1,436.2,429.6
XS GIS Cut Line= 4
     1724339.837       121755.89     1724130.634      121226.542
     1724175.141       120895.92     1724069.989      120447.815
#Sta/Elev= 30
      10 1620.94      30  1615.4    89.9 1603.62   199.7 1570.73   259.6 1555.25
   319.5 1537.81   419.4  1516.5   479.3 1501.91   509.3 1498.33   569.2 1486.97
   589.4 1480.78   619.7 1467.91   629.8  1465.2   718.4 1456.79   730.9 1455.17
     741 1456.02   743.4 1457.22   771.4 1473.12   842.1 1509.01   912.8 1547.98
   952.8 1567.55   972.8 1575.82  1002.9 1586.01  1072.9 1601.57  1082.9  1604.5
  1102.9 1613.35  1162.9 1643.43    1263 1695.86    1323 1732.31  1363.1 1759.71
#Mann= 3 , 0 , 0
       0     .08       0   718.4    .045       0   743.4      .1       0
Bank Sta=718.4,743.4
XS Rating Curve= 0 ,0
Exp/Cntr=0.3,0.1

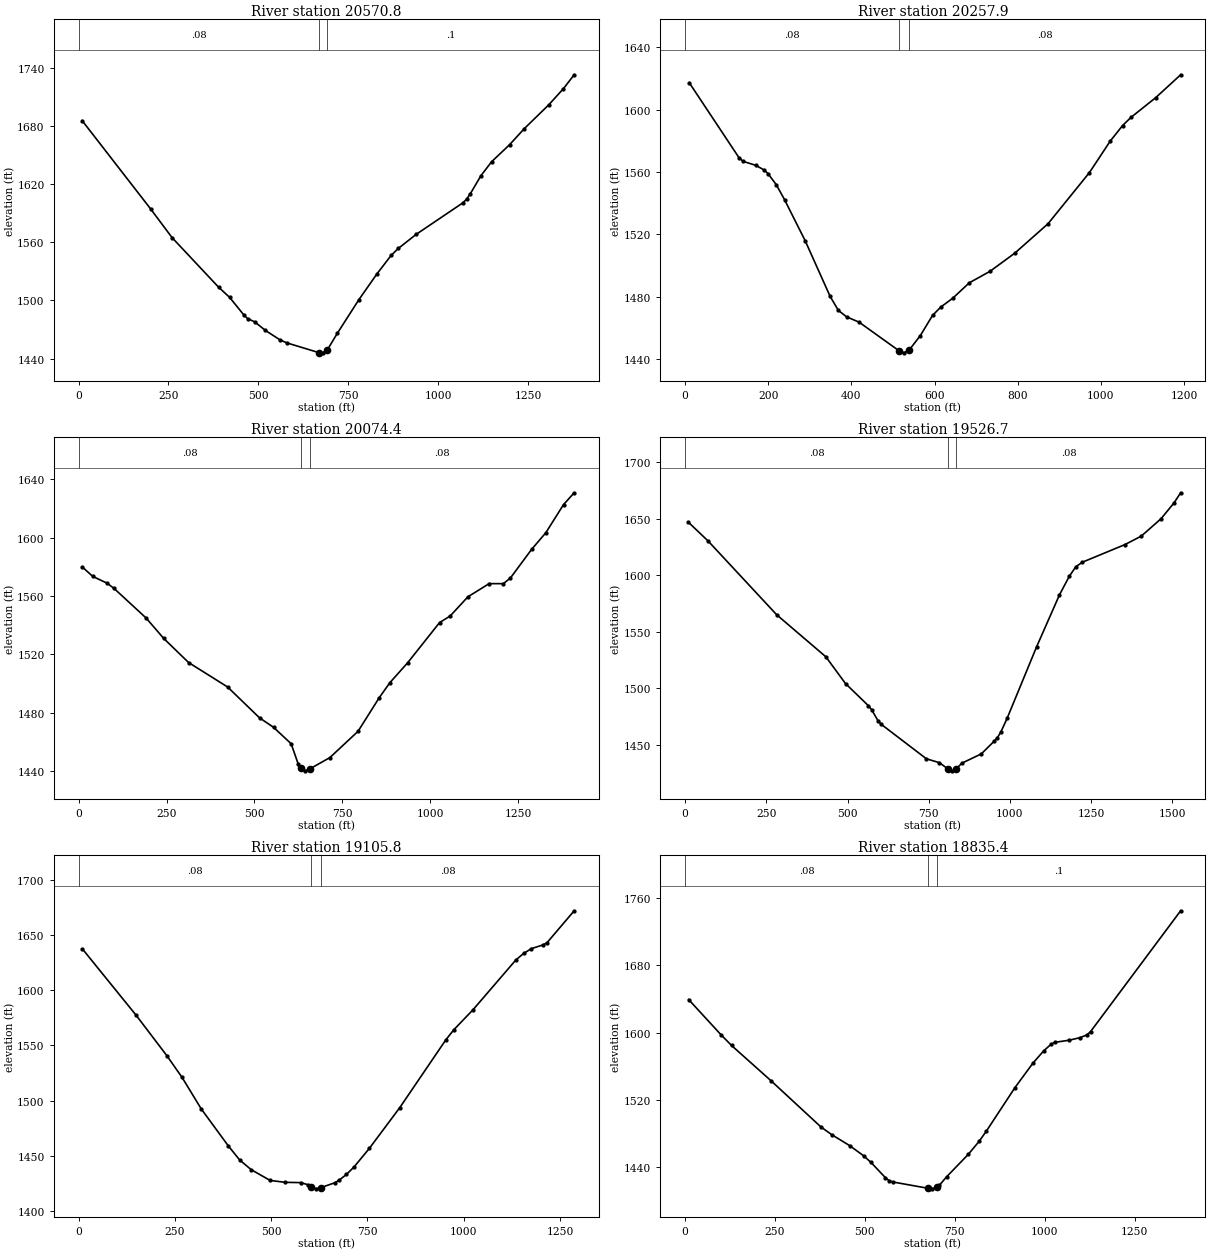
Type RM Length L Ch R = 1 ,20570.8 ,309.5,312.9,316.2
XS GIS Cut Line= 3
     1724654.198      121694.878     1724575.047      121009.562
      1724504.49      120324.325
#Sta/Elev= 30
      10 1685.31     200 1594.52     260 1564.76   389.9 1513.48   419.9 1503.25
   459.9 1484.94   469.9 1481.35   489.9  1477.9   519.9 1469.04   559.9 1459.42
   579.9 1456.18   667.4 1446.32   679.9 1445.99   692.4  1449.3   719.8 1466.17
   779.7  1500.8   829.6  1527.2   869.6 1546.51   889.5 1553.67   939.5 1568.25
  1069.2 1600.67  1079.2 1604.37  1089.2 1609.64  1119.2  1628.6  1149.1 1643.07
    1199 1660.57    1239  1676.8  1308.8 1701.99  1348.8 1718.38  1378.7 1732.67
#Mann= 3 , 0 , 0
       0     .08       0   667.4    .045       0   692.4      .1       0
Bank Sta=667.4,692.4
XS Rating Curve= 0 ,0
Exp/Cntr=0.3,0.1

Type RM Length L Ch R = 1 ,20257.9 ,203.5,183.5,163.5
XS GIS Cut Line= 4
      1724989.42      121537.118     1724887.973      121100.272
     1724890.043      120884.955      1724699.57       120392.21
#Sta/Elev= 30
      10 1617.37   129.6 1569.25   139.5 1566.88   169.4 1564.37   189.4 1561.45
   199.3 1559.04   219.3 1551.91   239.2  1542.3     289 1515.83   348.8 1480.22
   368.7 1471.18   388.7 1467.02   418.6 1463.62   514.3 1445.31   526.8 1443.93
   539.3  1445.8   565.9 1455.01   595.3 1467.97   614.9 1473.28   644.2 1479.07
   683.7  1488.9   733.6 1496.28   793.4 1507.99   873.1 1526.83   972.8 1559.71
  1022.6 1579.84  1052.5 1589.88  1072.5 1595.08  1132.3 1607.81  1192.1 1622.46
#Mann= 3 , 0 , 0
       0     .08       0   514.3    .045       0   539.3     .08       0
Bank Sta=514.3,539.3
XS Rating Curve= 0 ,0
Exp/Cntr=0.3,0.1

Type RM Length L Ch R = 1 ,20074.4 ,537.3,547.7,558.1
XS GIS Cut Line= 4
     1725227.133      121609.532     1725144.807      121101.853
     1724980.154       120900.61     1724815.501      120287.736
#Sta/Elev= 30
    10.1    1580    40.3 1573.46    80.7 1568.87   100.8 1565.22   191.6 1545.03
     242 1530.96   312.6 1514.48   423.6 1497.71   514.3 1476.58   554.3 1470.06
   604.3 1458.81   624.3 1444.94   631.8 1441.89   644.3 1440.27   656.8 1441.53
   714.3 1449.34   794.5 1467.38   854.9 1490.48   885.1 1500.72   935.5 1514.33
  1026.2 1541.85  1056.4 1546.37  1106.7 1559.49  1167.2 1568.54  1207.5 1568.51
  1227.6 1572.38  1288.1 1592.06  1328.4 1603.44  1378.7  1622.7  1408.9 1630.78
#Mann= 3 , 0 , 0
       0     .08       0   631.8    .045       0   656.8     .08       0
Bank Sta=631.8,656.8
XS Rating Curve= 0 ,0
Exp/Cntr=0.3,0.1

Type RM Length L Ch R = 1 ,19526.7 ,428.7,420.8,412.9
XS GIS Cut Line= 4
      1725867.45      121486.043     1725565.586      121033.247
     1725423.802      120598.747      1725153.81      120149.349
#Sta/Elev= 30
    10.1 1646.86    70.5 1630.34   282.2  1564.9   433.3 1527.78   493.8  1504.1
   564.1 1484.53     574 1481.06   593.9 1471.19   603.8 1468.01   742.9  1437.5
   782.7 1434.09   809.9 1428.38   822.4 1426.85   834.9 1428.73   852.2 1433.66
   911.8 1441.84   951.6  1453.1   961.5 1456.32   971.4 1460.82   991.3 1473.28
  1081.9 1536.49  1152.5 1582.59  1182.7 1598.98  1202.9  1607.5    1223 1611.48
  1354.1 1627.08  1404.5 1634.59    1465  1649.9  1505.3 1664.04  1525.5 1672.92
#Mann= 3 , 0 , 0
       0     .08       0   809.9    .045       0   834.9     .08       0
Bank Sta=809.9,834.9
XS Rating Curve= 0 ,0
Exp/Cntr=0.3,0.1

Type RM Length L Ch R = 1 ,19105.8 ,267.2,270.4,273.6
XS GIS Cut Line= 4
     1726187.608      121097.279     1725936.055       120726.81
     1725679.928      120338.047     1725487.833      120017.888
#Sta/Elev= 30
      10 1637.26   149.3 1577.33   228.9 1540.83   268.7 1521.02   318.4 1492.57
   388.1 1459.37   417.9 1446.46   447.8 1437.66   497.3 1427.84   536.9 1426.13
   576.6 1425.89   596.4 1423.88   603.7  1422.1   616.2 1420.25   628.7 1421.32
   665.7 1425.81   675.6 1427.86   695.4 1433.28   715.2 1440.09   754.9 1456.87
   834.1 1493.85   953.7  1555.2   973.9 1564.08  1024.4 1582.44  1135.4 1627.41
  1155.5 1633.25  1175.7 1637.63    1206 1641.01  1216.1 1642.94  1286.7 1671.87
#Mann= 3 , 0 , 0
       0     .08       0   603.7    .045       0   628.7     .08       0
Bank Sta=603.7,628.7
XS Rating Curve= 0 ,0
Exp/Cntr=0.3,0.1

Type RM Length L Ch R = 1 ,18835.4 ,565.1,562.5,559.7
XS GIS Cut Line= 3
     1726333.919      121075.886     1726146.445      120594.173
     1725757.681      119825.793
#Sta/Elev= 30
     9.9 1639.28    99.4 1597.61   129.2 1584.63   238.6 1542.81   377.7 1487.74
   407.6 1478.56   457.3  1465.6     497 1453.23   516.9 1445.52     557 1427.35
     567 1423.92     577  1422.3   674.6 1414.81   687.1 1414.08   699.6 1415.85
   707.2 1418.37   727.2 1428.41   787.3 1455.02   817.3 1470.43   837.3 1482.45
   917.4 1534.61   967.5 1563.76   997.5 1578.38  1017.6 1586.06  1027.6 1588.34
  1067.6  1590.9  1097.7 1593.89  1117.7  1597.3  1127.7 1601.26    1378 1744.91
#Mann= 3 , 0 , 0
       0     .08       0   674.6    .045       0   699.6      .1       0
Bank Sta=674.6,699.6
XS Rating Curve= 0 ,0
Exp/Cntr=0.3,0.1

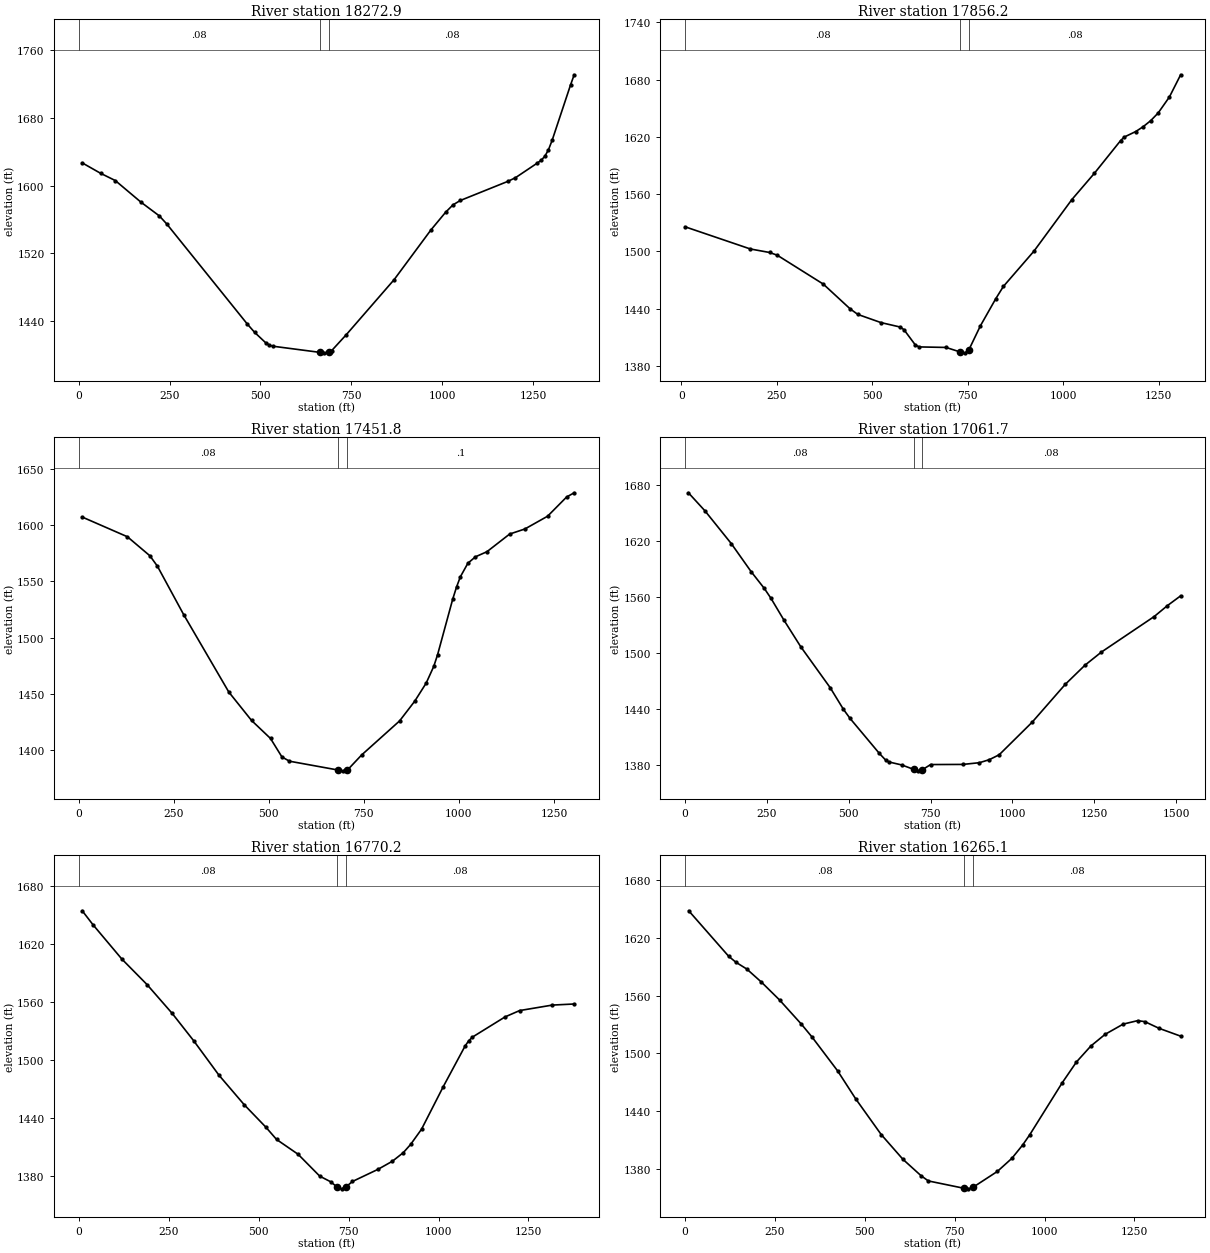
Type RM Length L Ch R = 1 ,18272.9 ,420.9,416.7,412.8
XS GIS Cut Line= 3
     1726951.414      120827.431     1726593.169      120254.324
     1726222.362      119675.773
#Sta/Elev= 30
    10.1 1626.68    60.5 1614.41   100.9 1605.85   171.5 1580.32   221.9 1564.15
   242.1 1554.74     464 1436.38   484.2 1426.54   514.5 1414.29   524.6 1411.46
   534.6 1410.21   663.4 1402.97   675.9  1402.4   688.4 1403.05   696.1 1405.07
   736.5 1423.98   867.9  1488.9   968.9 1547.49  1009.3 1568.38  1029.6 1577.14
  1049.8 1582.31  1181.1 1604.99  1201.4 1609.19    1262 1626.62  1272.1 1629.81
  1282.2 1634.44  1292.3 1642.23  1302.4 1653.41  1352.9 1718.62    1363 1730.78
#Mann= 3 , 0 , 0
       0     .08       0   663.4    .045       0   688.4     .08       0
Bank Sta=663.4,688.4
XS Rating Curve= 0 ,0
Exp/Cntr=0.3,0.1

Type RM Length L Ch R = 1 ,17856.2 ,394.1,404.4,414.6
XS GIS Cut Line= 4
     1727344.752      120585.026      1726983.43      120077.346
     1726754.746      119812.072     1726535.209      119560.519
#Sta/Elev= 30
    10.1 1525.67   180.9 1502.43   231.2 1498.76   251.3 1495.91   371.9 1465.61
   442.2 1439.64   462.3 1433.84   522.6 1425.32   572.9 1420.65   582.9 1417.91
   613.1 1401.67   623.1 1399.81   693.2 1399.25   730.7 1394.42   743.2  1393.6
   753.2 1397.03   783.2    1422   823.3 1450.33   843.3 1463.23   923.3 1500.19
  1022.5 1554.22  1081.4 1581.73  1150.1 1616.03  1159.9 1619.78  1189.4 1625.44
    1209 1630.52  1228.7 1636.85  1248.3  1644.9  1277.8 1661.71  1307.2 1684.97
#Mann= 3 , 0 , 0
    10.1     .08       0   730.7    .045       0   753.2     .08       0
Bank Sta=730.7,753.2
XS Rating Curve= 0 ,0
Exp/Cntr=0.3,0.1

Type RM Length L Ch R = 1 ,17451.8 ,396.5,390.1,383.8
XS GIS Cut Line= 4
     1727478.126      120455.652     1727363.047      120109.362
     1727198.394      119638.272     1726841.646      119382.145
#Sta/Elev= 30
     9.9 1606.99   128.2 1589.59   187.4  1572.7   207.1 1563.51   276.1 1520.58
   394.9 1451.83   454.7 1426.63   504.6 1410.63   534.6 1394.26   554.5 1390.47
   681.8 1382.67   694.3 1381.93   706.8 1382.62   744.2 1396.01     844 1426.21
   883.9 1443.75   913.9 1459.75   933.8 1474.53   943.8  1484.8   983.7 1534.23
   993.7 1544.89  1003.7 1553.98  1023.6 1566.09  1043.6 1571.82  1073.6 1576.29
  1133.4 1591.97  1173.4 1596.46  1233.2  1607.8  1283.2 1624.83  1303.1 1628.59
#Mann= 3 , 0 , 0
       0     .08       0   681.8    .045       0   706.8      .1       0
Bank Sta=681.8,706.8
XS Rating Curve= 0 ,0
Exp/Cntr=0.3,0.1

Type RM Length L Ch R = 1 ,17061.7 ,287.1,291.5,295.8
XS GIS Cut Line= 3
     1727706.073      120356.341     1727550.568       119574.24
     1726937.693      119267.803
#Sta/Elev= 30
    10.1 1671.38    60.5 1652.11   141.1 1616.96   201.6 1586.98   241.9    1569
   262.1 1558.49   302.4 1534.75   352.8 1506.77   443.5 1462.53   483.8 1439.41
     504 1429.73   593.3 1392.32   612.9 1385.05   622.7 1383.16   661.9 1379.94
   698.3 1375.24   710.8 1373.66   723.3 1374.56     750 1380.39   848.6 1380.53
     899 1382.38   929.2 1385.61   959.4 1390.87  1060.2 1425.78    1161  1466.2
  1221.4 1486.78  1271.8 1500.87    1433 1538.91  1473.3 1550.59  1513.6 1561.02
#Mann= 3 , 0 , 0
       0     .08       0   698.3    .045       0   723.3     .08       0
Bank Sta=698.3,723.3
XS Rating Curve= 0 ,0
Exp/Cntr=0.3,0.1

Type RM Length L Ch R = 1 ,16770.2 ,513.2,505.1,497
XS GIS Cut Line= 3
     1728191.479      120219.733     1727887.431      119611.488
     1727591.394      118980.459
#Sta/Elev= 30
      10 1654.53      40 1640.03     120 1604.58     190 1578.15     260 1548.27
     320 1519.83     390 1484.28     460 1453.78     520  1430.6     550 1417.77
     610 1402.39     670 1379.77   700.2 1373.99     718 1368.57   730.5 1366.64
     743 1368.73   760.8 1374.24   831.5 1386.76   871.9 1395.23   902.2 1404.12
   922.4 1412.56   952.8 1428.34  1013.4 1472.57    1074 1514.59  1084.1 1519.98
  1094.2 1523.72  1185.1 1544.68  1225.5 1551.22  1316.4  1556.9    1377 1558.02
#Mann= 3 , 0 , 0
       0     .08       0     718    .045       0     743     .08       0
Bank Sta=718,743
XS Rating Curve= 0 ,0
Exp/Cntr=0.3,0.1

Type RM Length L Ch R = 1 ,16265.1 ,480.8,492.1,502.7
XS GIS Cut Line= 4
     1728675.696      120027.036     1728460.732      119514.782
     1728232.048      119258.656     1727971.347      118856.171
#Sta/Elev= 30
    10.1 1648.12   121.2  1600.9   141.4 1594.69   171.7 1587.63   212.1 1574.16
   262.6 1555.61   323.2 1530.57   353.5  1516.9   424.2 1482.01   474.7 1452.85
   545.4 1415.92     606 1390.16   656.5 1373.11   676.7 1367.73   775.3 1360.15
   787.8 1359.54   800.3 1361.03   868.6  1377.6   908.9 1391.17   938.9    1405
   958.8 1415.73  1048.7 1469.45  1088.7 1491.26  1128.7 1507.79  1168.6 1519.96
  1218.6  1530.5  1258.5 1534.06  1278.5 1533.11  1318.5 1526.11  1378.4    1518
#Mann= 3 , 0 , 0
       0     .08       0   775.3    .045       0   800.3     .08       0
Bank Sta=775.3,800.3
XS Rating Curve= 0 ,0
Exp/Cntr=0.3,0.1