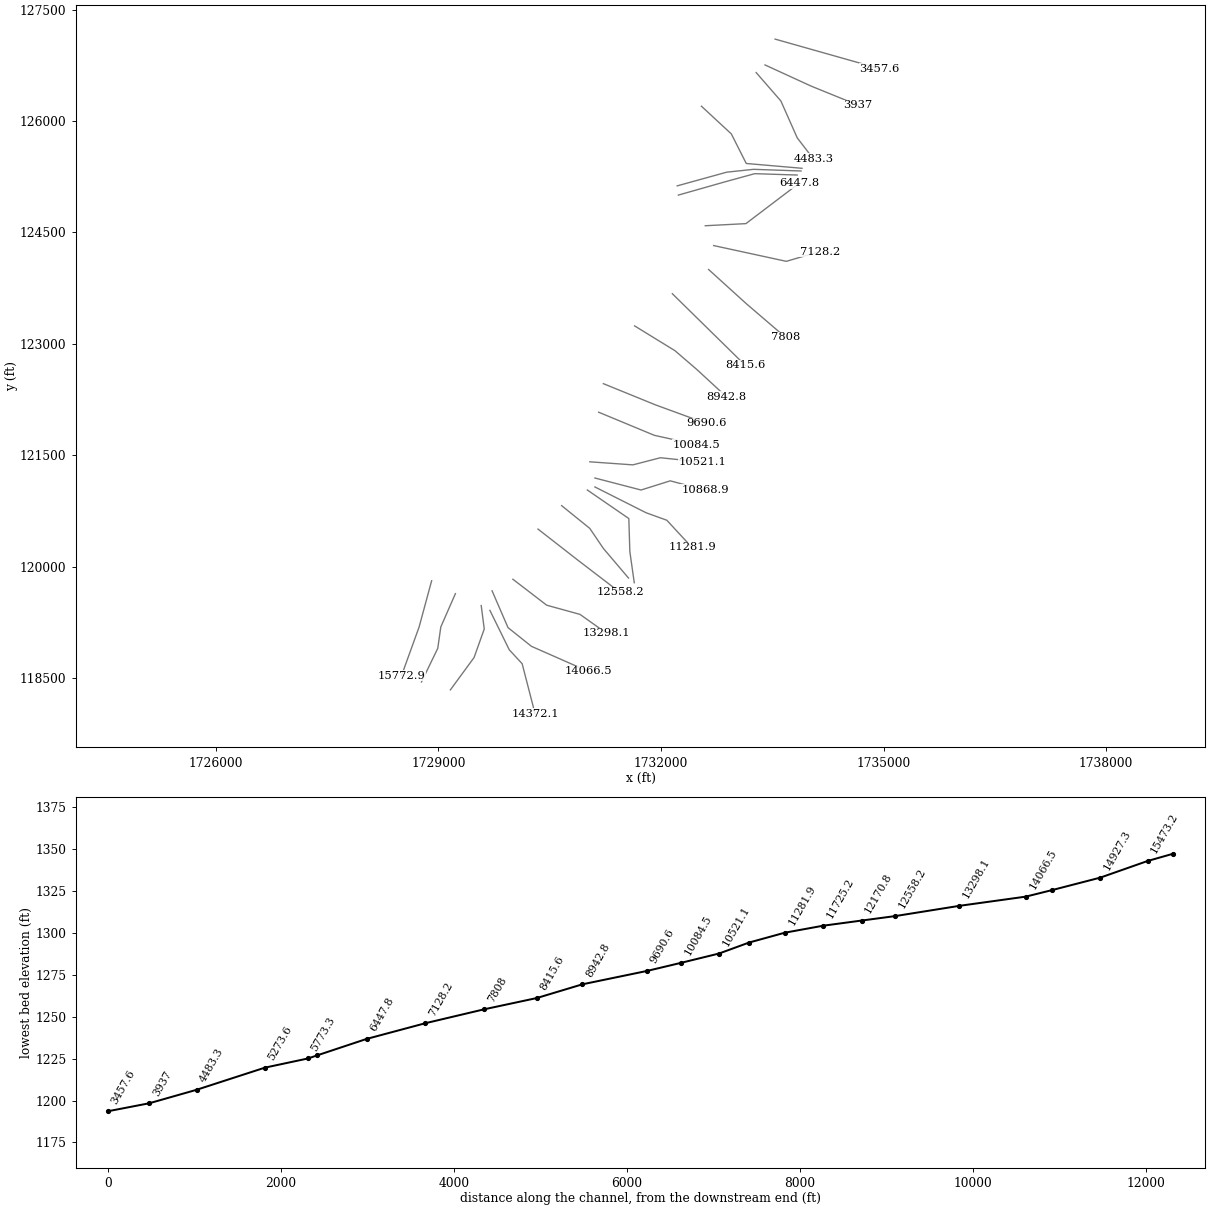
HEC-RAS study Bradshaw Creek.prj: Bradshaw Creek

--- Bradshaw Creek.g01 (geometry) --- (continued)

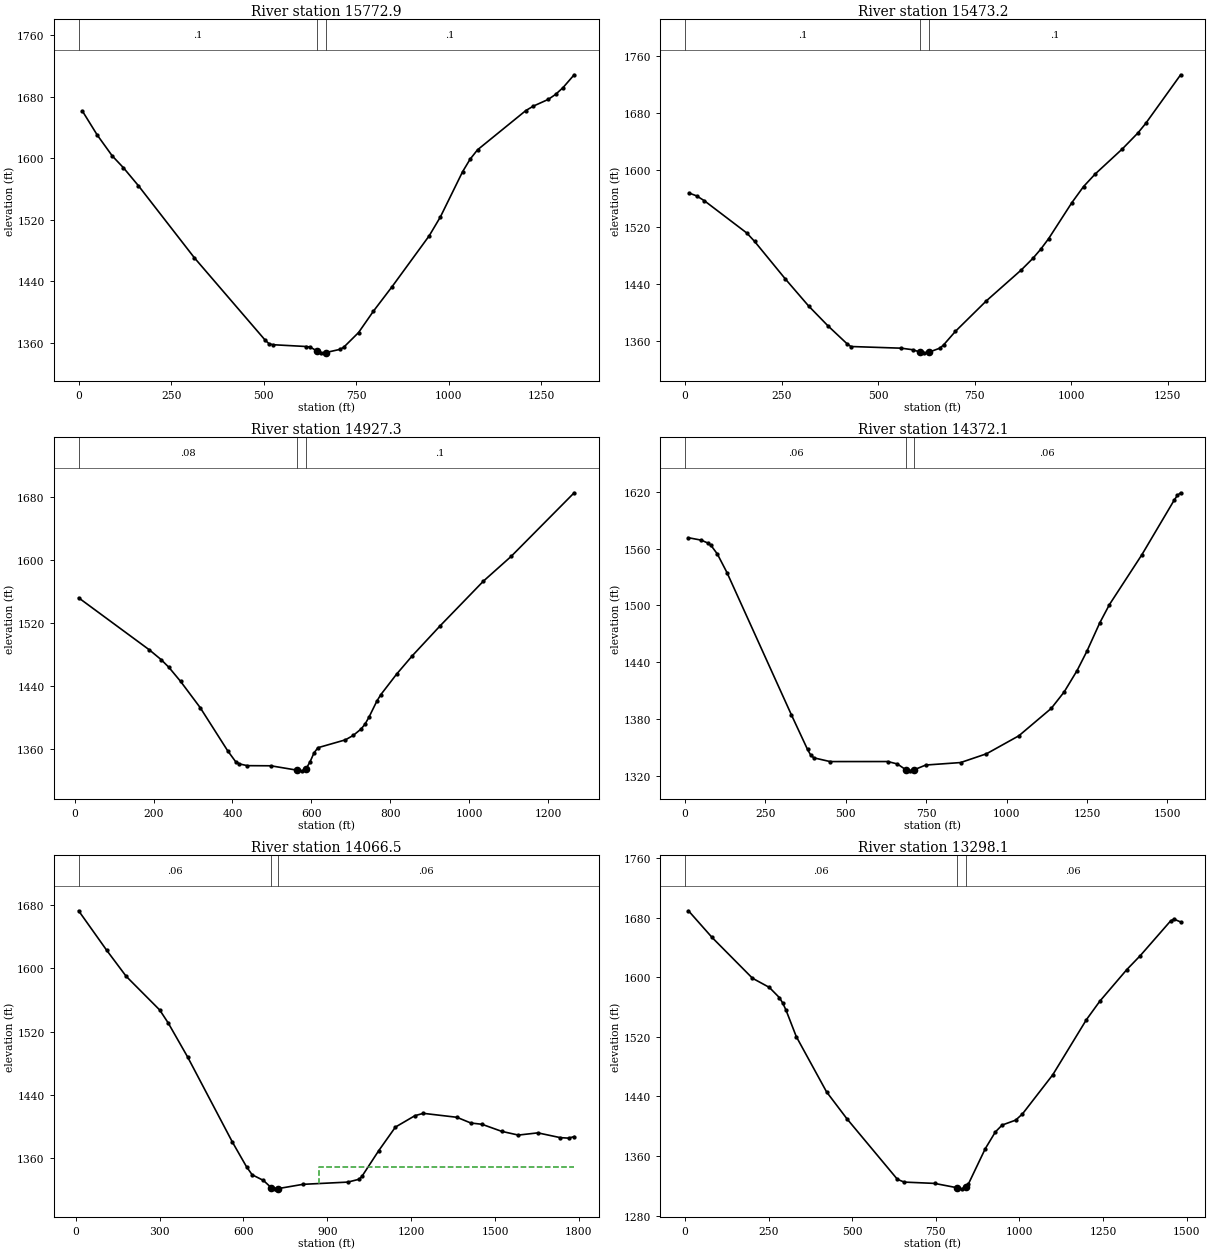
Type RM Length L Ch R = 1 ,15772.9 ,294.8,299.7,305.4
XS GIS Cut Line= 3
     1728908.954      119812.072     1728739.603       119188.49
     1728503.593      118536.451
#Sta/Elev= 30
    10.1 1661.61    50.5 1630.23    90.9 1603.24   121.2  1587.8   161.5 1564.58
     313 1470.74   504.8 1363.43   514.9 1359.05     525  1357.8   615.9 1355.43
     626 1354.72   643.7 1349.78   656.2 1347.23   668.7 1347.66   706.5 1351.75
   716.5 1354.45   756.7 1373.59   796.9 1401.38   847.2 1433.15   947.7 1499.39
   977.8 1523.79  1038.1 1582.81  1058.2 1598.92  1078.3 1611.15    1209 1662.21
  1229.1 1667.93  1269.3 1676.63  1289.4  1683.2  1309.5 1692.06  1339.6  1708.7
#Mann= 3 , 0 , 0
       0      .1       0   643.7    .045       0   668.7      .1       0
Bank Sta=643.7,668.7
XS Rating Curve= 0 ,0
Exp/Cntr=0.3,0.1

Type RM Length L Ch R = 1 ,15473.2 ,551.1,546,540.8
XS GIS Cut Line= 4
     1729229.112      119638.272     1729032.444       119190.05
      1728991.28      118901.908     1728771.743      118449.112
#Sta/Elev= 30
      10 1567.85      30 1563.75    49.9 1556.93   159.8 1511.53   179.8 1499.83
   259.7  1446.8   319.7 1408.95   369.6  1381.1   419.5 1355.61   429.5 1351.74
   559.7 1349.38   589.8  1347.2   607.4  1344.1   619.9 1342.83   632.4  1343.9
   660.1 1349.43   670.1 1354.28   700.2 1373.04   780.5 1416.06   871.1 1459.62
   901.3 1476.04   921.4 1488.78   941.6 1503.47    1002 1554.32  1032.1 1576.85
  1062.3 1594.55  1132.8 1629.96    1173 1652.33  1193.2 1665.79  1283.7 1734.25
#Mann= 3 , 0 , 0
       0      .1       0   607.4    .045       0   632.4      .1       0
Bank Sta=607.4,632.4
XS Rating Curve= 0 ,0
Exp/Cntr=0.3,0.1

Type RM Length L Ch R = 1 ,14927.3 ,524.5,555.2,585.7
XS GIS Cut Line= 4
     1729576.713      119478.193     1729617.876      119162.608
     1729480.665      118778.418     1729161.173       118342.63
#Sta/Elev= 30
     9.9    1552     189 1486.19   218.8 1473.89   238.7 1464.04   268.5 1446.14
   318.3 1412.87   387.9  1358.3   407.8 1344.72   417.8 1341.65   437.7 1339.49
   497.4 1339.31   564.5  1333.7     577 1332.92   586.9 1335.69   596.9 1344.47
   606.8 1355.59   616.8 1362.21   686.4 1372.16   706.3 1377.77   726.2 1385.88
   736.2 1392.06   746.2 1400.86   766.2  1421.2   776.2 1429.36   816.3 1455.37
   856.3 1478.75   926.3 1516.34  1036.4  1573.1  1106.5 1604.32  1266.6 1684.99
#Mann= 3 , 0 , 0
     9.9     .08       0   564.5    .045       0   586.9      .1       0
Bank Sta=564.5,586.9
XS Rating Curve= 0 ,0
Exp/Cntr=0.3,0.1

Type RM Length L Ch R = 1 ,14372.1 ,299.7,305.5,311.1
XS GIS Cut Line= 4
     1729694.098      119413.134     1729954.798      118882.586
     1730128.598      118695.065     1730302.399      118022.732
#Sta/Elev= 30
      10 1571.49    50.1 1568.93    70.1 1565.96    80.2 1563.52   100.2 1554.36
   130.3 1534.66   330.6 1384.62   380.7 1348.14   390.8 1342.03   400.8  1339.2
   450.9 1335.29   630.5 1335.32     660 1332.78   686.8  1326.6   699.3 1325.51
   711.8 1326.56   748.5 1331.63   856.9 1334.25   937.4 1343.51    1038 1362.49
  1138.7 1391.38  1178.9 1408.73  1219.2 1431.37  1249.4 1451.52  1289.6 1481.59
  1319.8 1500.96  1420.5 1553.46  1521.1 1611.11  1531.2 1616.17  1541.2  1618.9
#Mann= 3 , 0 , 0
       0     .06       0   686.8    .045       0   711.8     .06       0
Bank Sta=686.8,711.8
XS Rating Curve= 0 ,0
Exp/Cntr=0.3,0.1

Type RM Length L Ch R = 1 ,14066.5 ,756.9,768.5,780.1
XS GIS Cut Line= 4
     1729723.253      119676.554     1729938.034      119180.903
     1730253.619       118929.35     1731021.999      118590.897
#Sta/Elev= 30
      10 1672.66     110 1622.99   180.1 1589.94   300.1 1547.42   330.1  1531.3
   400.1 1488.04   560.4 1380.56   610.8 1349.47     631 1339.35   671.3 1332.22
   699.2 1323.05   711.7 1321.59   724.2  1321.9   812.6 1327.27   973.7 1330.11
  1013.7  1333.7  1023.7 1337.26  1083.7 1369.66  1143.7 1399.57  1213.6 1413.98
  1243.6 1416.91  1363.6 1411.93  1413.5 1404.71  1453.5 1403.09  1523.5 1394.23
  1583.5 1389.46  1653.4 1392.26  1733.4 1386.26  1763.4  1385.6  1783.4 1387.54
#Mann= 3 , 0 , 0
      10     .06       0   699.2    .045       0   724.2     .06       0
#XS Ineff= 2 , 0
                           870.5         1349.37
Permanent Ineff=
       F       F
Bank Sta=699.2,724.2
XS Rating Curve= 0 ,0
Exp/Cntr=0.3,0.1

Type RM Length L Ch R = 1 ,13298.1 ,750.6,739.9,729.4
XS GIS Cut Line= 4
      1730003.65      119832.092     1730459.435      119482.766
     1730907.657      119359.277     1731268.978       119103.15
#Sta/Elev= 30
    10.1 1689.04    80.6 1653.29   201.5 1598.58   251.9 1586.28   282.1 1572.53
   292.2 1565.14   302.2 1555.38   332.5 1520.32   423.1 1446.15   483.6 1410.29
   634.9 1328.89   655.1 1325.14   746.1 1323.38   814.4 1317.48   826.9 1316.09
   839.4 1318.34   847.1 1322.35   897.7 1369.87     928 1392.41   948.2 1401.62
   988.6 1408.23  1008.9  1416.5  1099.6 1469.03  1200.2 1542.93  1240.5 1567.84
    1321 1610.11  1361.3 1628.83  1451.9 1675.34  1461.9 1677.88  1482.1 1674.03
#Mann= 3 , 0 , 0
       0     .06       0   814.4    .045       0   839.4     .06       0
Bank Sta=814.4,839.4
XS Rating Curve= 0 ,0
Exp/Cntr=0.3,0.1

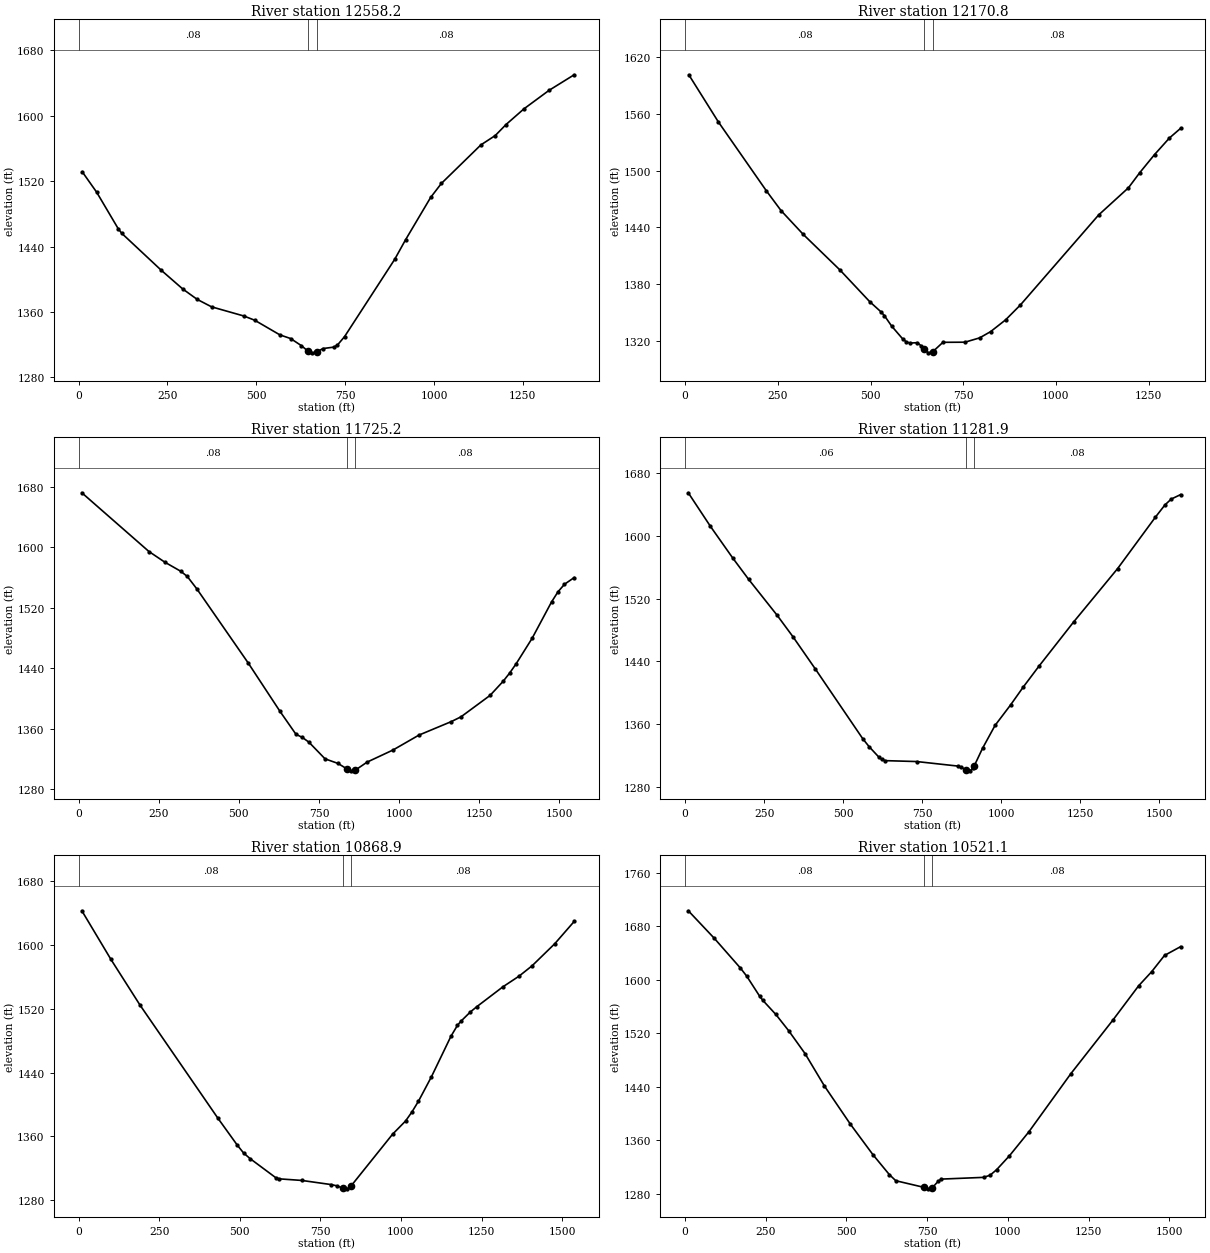
Type RM Length L Ch R = 1 ,12558.2 ,396.2,387.4,378.4
XS GIS Cut Line= 3
     1730341.996      120507.478     1730884.472      120084.975
     1731446.149      119655.911
#Sta/Elev= 30
    10.1 1531.39    50.6 1506.46   111.2  1461.9   121.3 1456.13   232.6 1410.92
   293.2 1387.98   333.7 1375.33   374.1 1366.23   465.1 1355.01   495.5 1349.85
   566.3 1331.95   596.6 1327.46   626.9 1318.75   644.8 1312.27   657.3 1309.99
   669.8 1311.13   687.6 1315.24   717.9 1316.96     728 1319.38   748.2 1329.76
   889.5 1424.39   919.8 1448.13   990.5 1499.96  1020.8 1517.13  1131.9 1564.21
  1172.3 1575.64  1202.6 1589.08    1253 1608.27  1323.7 1630.91  1394.4 1649.95
#Mann= 3 , 0 , 0
       0     .08       0   644.8    .045       0   669.8     .08       0
Bank Sta=644.8,669.8
XS Rating Curve= 0 ,0
Exp/Cntr=0.3,0.1

Type RM Length L Ch R = 1 ,12170.8 ,461.2,445.6,430.1
XS GIS Cut Line= 4
     1730660.677      120822.858     1731040.294       120516.42
     1731223.241      120246.573     1731561.694      119848.662
#Sta/Elev= 30
      10 1601.21    89.6 1551.44     219 1478.65   258.9 1457.59   318.6 1432.51
   418.2 1394.66   497.7 1361.48   527.4 1350.95   537.3 1346.71     557 1335.61
   586.7 1322.07   596.5 1318.92   606.4 1317.68   626.2 1318.05   636.1 1314.94
   643.3 1311.43   655.8 1307.33   668.3 1308.68   695.3 1318.45   754.6 1318.58
   794.1 1323.12   823.9 1329.76   864.1 1342.13   904.3 1357.97  1115.3 1453.11
  1195.6  1481.8  1225.8 1497.62  1265.9 1516.86  1306.1 1534.41  1336.3 1544.64
#Mann= 3 , 0 , 0
       0     .08       0   643.3    .045       0   668.3     .08       0
Bank Sta=643.3,668.3
XS Rating Curve= 0 ,0
Exp/Cntr=0.3,0.1

Type RM Length L Ch R = 1 ,11725.2 ,409.9,443.3,476.7
XS GIS Cut Line= 4
     1731007.341       121033.13     1731566.268      120649.057
     1731579.872      120204.743     1731639.471      119785.168
#Sta/Elev= 30
      10 1671.95   219.4 1594.29   269.3  1580.1   319.1 1568.07   339.1 1561.29
     369 1544.82   528.6 1447.26   628.3 1382.97   678.2 1352.63   698.4 1348.36
   718.6 1342.19   769.1 1320.09   809.5 1314.05   837.4 1306.79   849.9 1304.25
   862.4 1304.86   900.4 1315.82   981.3 1331.84  1062.1 1351.52  1163.1 1369.37
  1193.3 1375.67  1284.1 1404.03  1324.5  1422.5  1344.7 1433.31  1364.9 1445.49
  1415.3 1479.54  1475.8 1527.52    1496    1541  1516.2 1550.94  1546.5 1559.82
#Mann= 3 , 0 , 0
       0     .08       0   837.4    .045       0   862.4     .08       0
Bank Sta=837.4,862.4
XS Rating Curve= 0 ,0
Exp/Cntr=0.3,0.1

Type RM Length L Ch R = 1 ,11281.9 ,394.9,413,431
XS GIS Cut Line= 4
     1731108.899      121074.411     1731799.526       120726.81
     1732078.521      120626.189     1732416.974      120260.294
#Sta/Elev= 30
      10 1655.31    80.3 1612.34   150.6 1572.06   200.8 1544.86   291.2 1498.85
   341.4 1471.37   411.7 1430.48   562.3 1341.06   582.4 1330.94   612.5 1317.91
   622.6 1314.66   632.6 1313.12     733 1311.95   862.1 1306.22     872 1305.16
   889.2 1301.13   901.7 1300.08   911.6 1303.66   914.2 1305.71   941.2 1328.79
   980.8 1358.05  1030.2 1384.37  1069.8 1406.96  1119.6 1433.67  1229.3 1490.15
  1368.8 1558.49  1488.4 1624.19  1518.3 1639.68  1538.3 1647.23  1568.2 1653.01
#Mann= 3 , 0 , 0
       0     .06       0   889.2    .045       0   914.2     .08       0
Bank Sta=889.2,914.2
XS Rating Curve= 0 ,0
Exp/Cntr=0.3,0.1

Type RM Length L Ch R = 1 ,10868.9 ,349.3,347.8,346.4
XS GIS Cut Line= 4
     1731109.376      121194.648     1731730.921      121033.247
     1732124.258      121156.737     1732591.105      121032.524
#Sta/Elev= 30
      10 1643.13   100.3 1582.06   190.6 1524.68   431.5 1383.18   491.7 1349.35
   511.7 1339.24   531.8 1332.19   612.1 1308.06   622.1 1306.75   692.4 1304.76
   782.9 1299.59     803 1297.84   820.7 1294.64   833.2 1294.21   845.7 1298.04
     974 1362.74  1014.2 1379.25  1034.3 1390.77  1054.4 1404.16  1094.7 1434.88
  1155.1  1485.6  1175.2 1499.26  1185.3  1504.2  1215.5 1516.19  1235.6 1522.84
  1316.1 1547.63  1366.4 1561.08  1406.7 1574.02  1477.1 1601.71  1537.5 1629.74
#Mann= 3 , 0 , 0
       0     .08       0   820.7    .045       0   845.7     .08       0
Bank Sta=820.7,845.7
XS Rating Curve= 0 ,0
Exp/Cntr=0.3,0.1

Type RM Length L Ch R = 1 ,10521.1 ,454.6,436.6,418.6
XS GIS Cut Line= 4
     1731040.294      121412.864     1731621.152      121371.701
     1731991.621      121467.748     1732558.759       121408.29
#Sta/Elev= 30
      10 1703.14    90.4 1662.03   170.7 1617.96   190.8 1605.55   230.9 1575.55
     241 1569.21   281.1 1548.27   321.3 1523.68   371.5 1489.84   431.7  1441.3
     512 1384.34   582.3 1338.48   632.7 1308.99   652.8 1299.78     741 1289.75
   753.5 1287.65     766 1289.32   783.7 1298.75   793.8  1302.2   924.7 1304.79
   944.9    1308     965 1316.16    1005  1337.1  1065.1 1372.86  1195.1 1459.71
  1325.2 1539.68  1405.2 1591.07  1445.2 1611.93  1485.3 1636.41  1535.3 1649.56
#Mann= 3 , 0 , 0
       0     .08       0     741    .045       0     766     .08       0
Bank Sta=741,766
XS Rating Curve= 0 ,0
Exp/Cntr=0.3,0.1

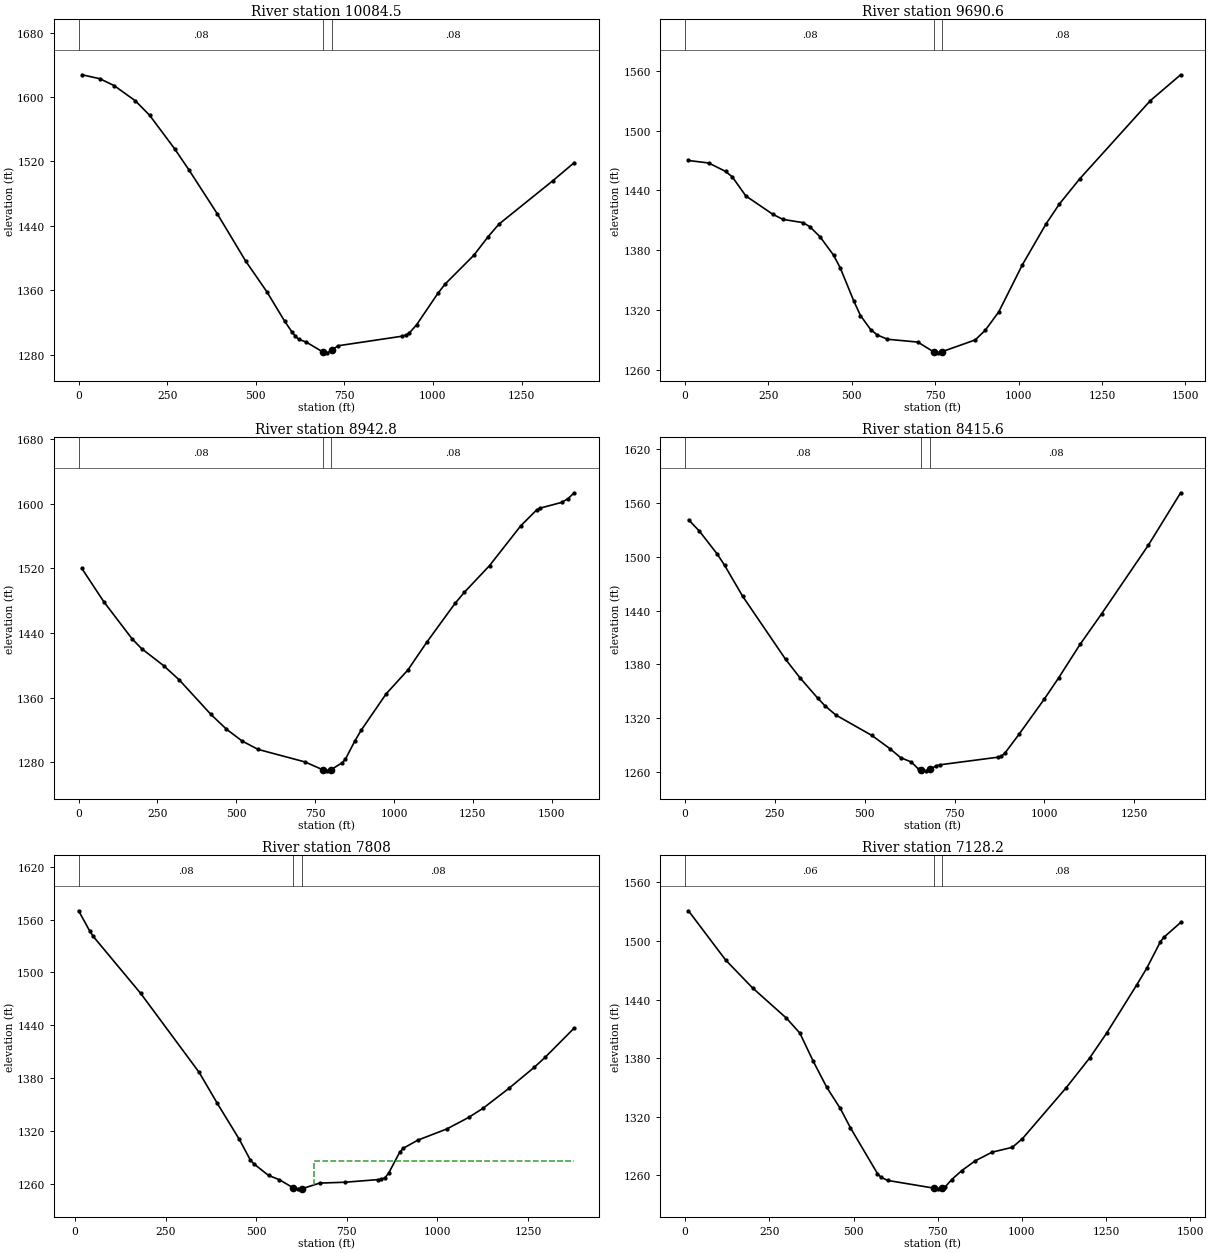
Type RM Length L Ch R = 1 ,10084.5 ,393.4,393.9,394.8
XS GIS Cut Line= 3
      1731159.21      122080.622     1731909.295      121769.611
     1732482.102      121642.967
#Sta/Elev= 30
      10 1627.62    60.1 1622.66   100.2 1614.18   160.4 1595.17   200.5 1577.22
   270.7 1535.79   310.8 1509.82     391 1455.12   471.2 1396.33   531.3 1357.97
   581.4 1321.49   601.5 1308.43   611.5 1302.83   621.5 1298.82   641.6  1295.7
   689.2 1283.25   701.7 1282.13   714.2 1285.23   731.8 1290.89   913.2 1302.81
   923.3 1304.06   933.4 1306.82   953.6 1316.82  1014.3 1356.27  1034.5 1367.65
  1115.4 1403.36  1155.9 1426.53  1186.2 1442.02    1338 1495.83  1398.6 1518.37
#Mann= 3 , 0 , 0
       0     .08       0   689.2    .045       0   714.2     .08       0
Bank Sta=689.2,714.2
XS Rating Curve= 0 ,0
Exp/Cntr=0.3,0.1

Type RM Length L Ch R = 1 ,9690.6  ,757.3,747.8,737.9
XS GIS Cut Line= 3
     1731223.241      122464.813     1731925.891      122179.024
     1732609.069      121929.691
#Sta/Elev= 30
    10.1 1470.06    70.8 1467.56   121.4 1459.11   141.6 1453.57   182.1 1434.55
     263 1416.15   293.3 1411.05     354 1407.75   374.2 1403.63   404.6  1393.6
     445 1375.24   465.2 1362.44   505.7 1329.34   525.9 1314.66   556.3 1300.64
   576.5 1295.16   606.8 1290.92   697.9 1288.07     746 1278.07   758.5 1277.29
     771 1278.52   869.7  1290.2     900 1299.94   940.4  1318.3  1011.1 1365.43
  1081.8 1406.27  1122.2 1426.44  1182.8 1451.53  1394.9 1530.05  1485.8 1555.97
#Mann= 3 , 0 , 0
       0     .08       0     746    .045       0     771     .08       0
Bank Sta=746,771
XS Rating Curve= 0 ,0
Exp/Cntr=0.3,0.1

Type RM Length L Ch R = 1 ,8942.8  ,528.8,527.2,525.6
XS GIS Cut Line= 4
     1731644.021       123242.34      1732188.29       122908.46
     1732481.006      122656.908     1732883.491      122286.439
#Sta/Elev= 30
      10 1519.85    79.8 1478.55   169.6  1432.6   199.5 1420.59   269.4 1399.47
   319.3 1381.75     419 1339.31   468.9  1320.8   518.8 1306.13   568.7 1295.88
   717.7 1280.33   774.5 1270.59     787  1269.3   799.5 1270.43   836.4  1279.5
   846.3 1283.94     876 1306.24   895.8 1319.37     975 1364.46  1044.4 1394.22
    1104 1428.42  1193.6 1476.43  1223.4 1490.29    1303  1523.2  1402.4 1572.62
  1452.2 1591.97  1462.1 1594.22  1531.7 1601.43  1551.6 1605.92  1571.5 1613.35
#Mann= 3 , 0 , 0
       0     .08       0   774.5    .045       0   799.5     .08       0
Bank Sta=774.5,799.5
XS Rating Curve= 0 ,0
Exp/Cntr=0.3,0.1

Type RM Length L Ch R = 1 ,8415.6  ,606.6,607.6,608.5
XS GIS Cut Line= 3
     1732152.826      123675.328     1732637.864      123199.378
     1733137.315      122710.053
#Sta/Elev= 30
      10  1541.2      40 1528.57    89.9 1502.82   109.9 1490.52   159.9 1456.12
   279.8 1385.48   319.8 1364.88   369.8 1341.88   389.7  1333.5   419.7 1323.34
   519.7  1300.6   569.6 1285.96   599.6 1275.86   629.6 1270.92   649.6 1262.99
   657.1 1261.61   669.6 1261.11   682.1 1263.09   699.5 1266.89   709.5 1267.88
   869.3 1276.27   879.3 1277.17   889.3 1280.59   929.3    1302   999.2 1341.08
  1039.1 1364.75  1099.1 1402.34    1159 1436.43  1288.9 1512.95  1378.8 1571.47
#Mann= 3 , 0 , 0
       0     .08       0   657.1    .045       0   682.1     .08       0
Bank Sta=657.1,682.1
XS Rating Curve= 0 ,0
Exp/Cntr=0.3,0.1

Type RM Length L Ch R = 1 ,7808    ,665.4,679.8,694.3
XS GIS Cut Line= 3
     1732641.085      124001.573     1733148.926      123541.672
     1733674.739      123091.408
#Sta/Elev= 30
    10.1  1569.9    40.3 1547.24    50.4 1540.83   181.4 1476.12   342.6 1386.56
   392.9 1351.27   453.4 1310.58   483.6 1287.32   493.7 1282.69     534 1269.63
   564.2 1264.71   602.1 1255.51   614.6  1254.4   627.1  1254.6   675.1 1260.91
   745.3  1261.9   835.6 1264.86   845.7 1265.29   855.7 1267.11   865.7 1272.39
   895.8  1295.8   905.9 1300.45     946 1309.64  1026.2 1322.39  1086.4 1335.46
  1126.6 1345.99  1196.8 1368.25    1267  1392.2  1297.1 1403.56  1377.4 1436.77
#Mann= 3 , 0 , 0
    10.1     .08       0   602.1    .045       0   627.1     .08       0
#XS Ineff= 2 , 0
                          658.82         1286.46
Permanent Ineff=
       F       F
Bank Sta=602.1,627.1
XS Rating Curve= 0 ,0
Exp/Cntr=0.3,0.1

Type RM Length L Ch R = 1 ,7128.2  ,656.5,680.4,704.3
XS GIS Cut Line= 3
      1732709.64      124323.551      1733688.46      124111.341
     1734139.047      124243.517
#Sta/Elev= 30
      10 1530.89   120.2  1480.5   200.3 1451.88   300.5 1421.02   340.5 1405.71
   380.6 1376.65   420.7 1349.97   460.7 1328.44   490.8 1308.63   570.9 1261.81
   580.9 1258.16   600.9 1254.74   738.7 1246.81   751.2  1246.1   763.7 1246.58
   771.2 1247.79   791.2 1255.49   821.3 1264.77   861.3 1274.79   911.4 1283.66
   971.5 1288.65  1001.6 1297.53  1131.4 1349.67  1201.4 1380.31  1251.3 1405.52
  1341.3 1455.27  1371.2 1472.52  1411.2 1499.29  1421.2 1503.71  1471.1 1518.89
#Mann= 3 , 0 , 0
       0     .06       0   738.7    .045       0   763.7     .08       0
Bank Sta=738.7,763.7
XS Rating Curve= 0 ,0
Exp/Cntr=0.3,0.1

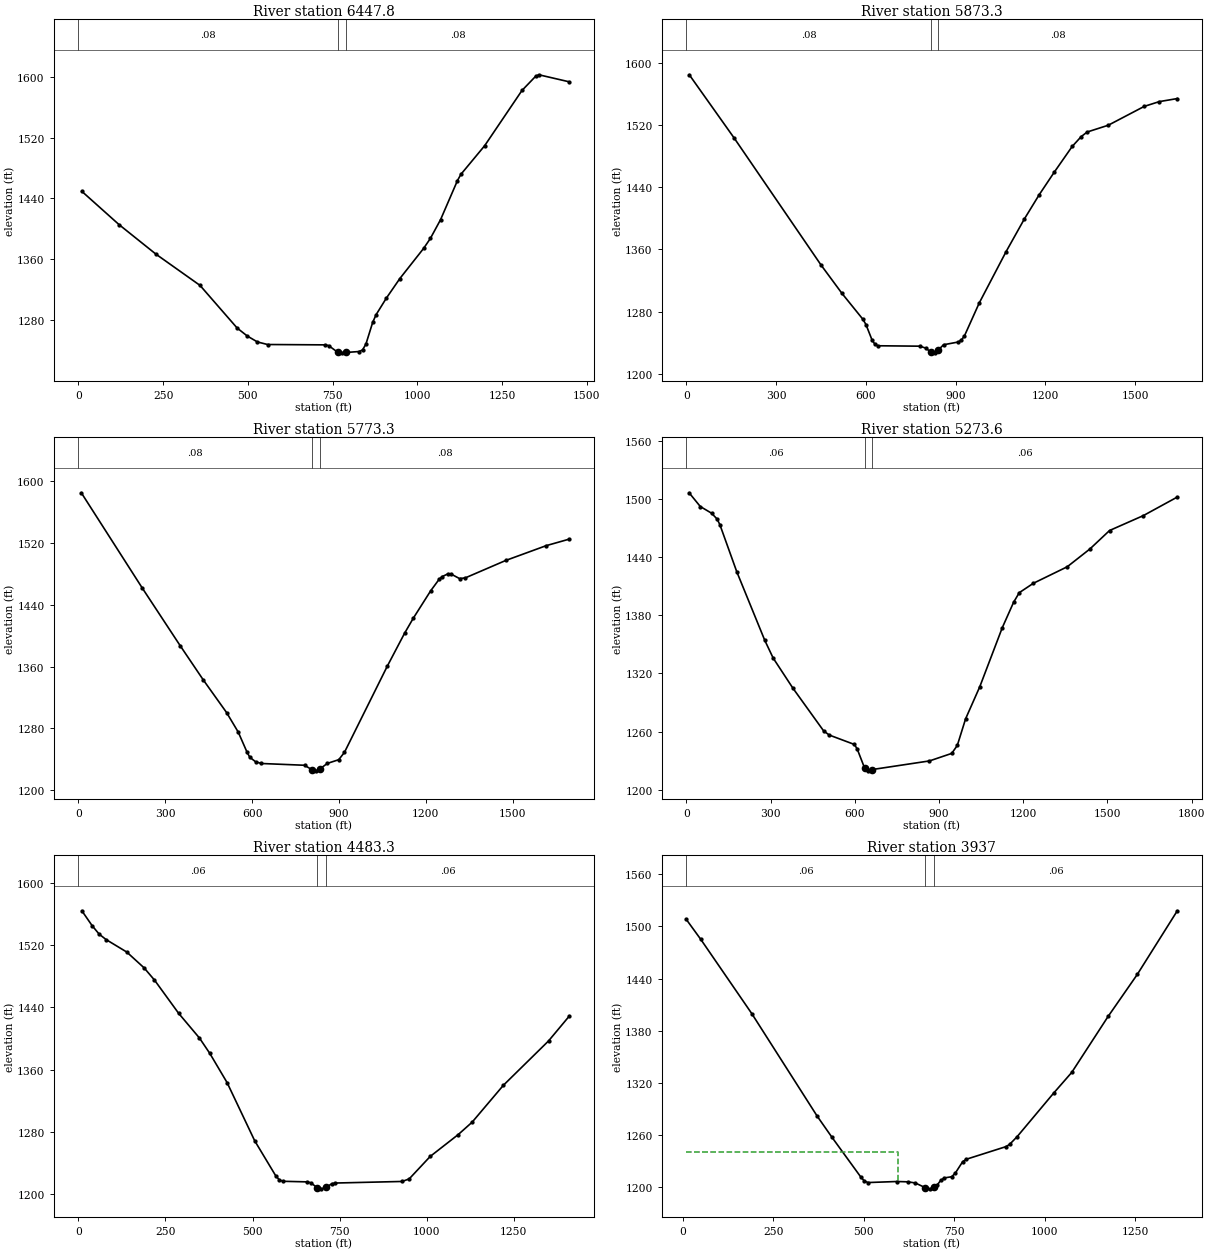
Type RM Length L Ch R = 1 ,6447.8  ,584.8,574.5,564.2
XS GIS Cut Line= 3
     1732596.649      124590.419     1733144.191      124619.021
     1733862.261       125163.29
#Sta/Elev= 30
      10 1449.39   119.6 1405.67   229.3  1366.5   358.9 1325.53   468.5 1269.39
   498.4 1258.87   528.4 1251.04   558.3 1247.68   728.5  1247.2   738.5 1246.26
   766.1 1237.26   778.6 1236.71   791.1 1237.25   828.6 1238.44   838.6 1240.57
   848.6 1248.14   868.7 1276.95   878.7 1286.95   908.7 1308.57   948.7 1334.48
  1018.8 1374.13  1038.8 1387.28  1068.9    1412  1118.9  1463.6    1129 1471.74
    1199 1509.36  1309.2 1582.12  1349.2 1600.66  1359.2 1602.81  1449.3 1593.48
#Mann= 3 , 0 , 0
       0     .08       0   766.1    .045       0   791.1     .08       0
Bank Sta=766.1,791.1
XS Rating Curve= 0 ,0
Exp/Cntr=0.3,0.1

Type RM Length L Ch R = 1 ,5873.3  ,104.6,100,95.4
XS GIS Cut Line= 4
     1732234.027      125003.211     1732878.917      125186.158
     1733263.107      125291.353     1733834.819      125273.058
#Sta/Elev= 30
      10 1584.47   160.1 1503.03   450.2 1339.81   520.3 1303.24   590.3 1269.93
   600.3 1263.24   620.3 1243.73   630.3 1237.76   640.3 1235.95   779.9 1235.42
   799.8 1233.02   817.2 1227.76   829.7 1226.85   842.2 1230.58   859.5 1237.24
   909.3 1240.81   919.3 1243.41   929.3 1248.53     979 1291.11  1068.7  1357.1
  1128.9 1398.55  1179.1 1430.14  1229.2 1459.03  1289.4 1492.27  1319.5 1504.94
  1339.6 1510.87  1409.9 1519.56  1530.3 1543.83  1580.5 1549.96  1640.7 1553.88
#Mann= 3 , 0 , 0
       0     .08       0   817.2    .045       0   842.2     .08       0
Bank Sta=817.2,842.2
XS Rating Curve= 0 ,0
Exp/Cntr=0.3,0.1

Type RM Length L Ch R = 1 ,5773.3  ,534,499.7,465.4
XS GIS Cut Line= 4
     1732218.158      125127.246      1732885.76      125311.631
     1733248.172       125349.78     1733887.163      125327.527
#Sta/Elev= 30
      10 1584.71   220.8 1461.43   351.3 1387.13   431.6  1342.6   511.9 1300.49
   552.1 1275.28   582.2 1249.59   592.2 1242.59   612.3 1236.83   632.4  1234.6
   781.2 1232.31   808.1 1226.26   820.6  1225.1   833.1  1227.2     860 1234.71
   899.4 1239.51   919.1 1248.98    1067 1360.34  1126.9 1403.06  1156.9 1422.45
  1216.9 1457.84  1246.8 1473.09  1256.8 1476.31  1276.8  1479.9  1286.8 1479.73
  1316.8 1473.76  1336.7 1474.65  1476.6 1497.22  1616.5 1516.36  1696.4 1524.84
#Mann= 3 , 0 , 0
       0     .08       0   808.1    .045       0   833.1     .08       0
Bank Sta=808.1,833.1
XS Rating Curve= 0 ,0
Exp/Cntr=0.3,0.1

Type RM Length L Ch R = 1 ,5273.6  ,791.6,790.3,788.9
XS GIS Cut Line= 4
     1732544.608      126199.531     1732947.523      125826.475
     1733148.765      125428.564      1733899.97      125363.747
#Sta/Elev= 30
      10 1506.19    49.9 1492.02    89.9 1485.16   109.8  1479.1   119.8 1473.19
   179.7 1424.87   279.5 1354.13   309.5  1335.8   379.4 1304.94   489.2 1260.76
   509.2 1256.49   598.6 1246.81   608.6 1242.25   635.7 1222.02   648.2  1219.6
   660.7 1220.87   866.2 1229.82   945.5 1237.58   965.3 1245.77     995 1273.32
  1045.3 1306.21  1125.7 1367.25  1165.9 1393.35    1186 1403.22  1236.3 1412.91
  1356.9 1429.92  1437.4  1448.2  1507.7  1467.3  1628.4 1482.72    1749  1501.8
#Mann= 3 , 0 , 0
       0     .06       0   635.7    .045       0   660.7     .06       0
Bank Sta=635.7,660.7
XS Rating Curve= 0 ,0
Exp/Cntr=0.3,0.1

Type RM Length L Ch R = 1 ,4483.3  ,526.3,546.3,567.4
XS GIS Cut Line= 4
     1733282.512      126651.891     1733615.281      126270.123
     1733836.101       125772.58     1734055.515      125487.928
#Sta/Elev= 30
     9.9 1564.55    39.7  1545.2    59.6 1534.47    79.4  1527.5     139 1511.36
   188.7 1491.01   218.5  1475.3     288  1432.4   347.6 1400.67   377.3 1380.91
     427 1343.25   506.4 1268.22   566.9 1223.06     577 1217.97   587.1 1216.11
   657.6 1215.34   667.7  1214.1   685.5 1207.95     698 1206.38   710.5 1208.28
   728.2    1213   738.3 1213.86   929.8 1215.89     950 1219.17  1010.5 1248.17
  1090.7 1276.22  1130.7  1292.2  1220.5 1339.75  1350.3 1396.92  1410.2 1429.11
#Mann= 3 , 0 , 0
       0     .06       0   685.5    .045       0   710.5     .06       0
Bank Sta=685.5,710.5
XS Rating Curve= 0 ,0
Exp/Cntr=0.3,0.1

Type RM Length L Ch R = 1 ,3937    ,475.2,479.4,482.4
XS GIS Cut Line= 3
     1733401.381       126754.94     1734021.684      126470.617
     1734654.746      126213.473
#Sta/Elev= 30
      10 1507.91    50.2 1484.89   190.7 1399.77   371.3 1281.93   411.4 1258.06
   491.7 1212.01   501.7 1207.35   511.8 1205.59     592 1206.79   622.2  1206.4
   642.2 1205.11   669.9 1199.69   682.4 1198.36   692.4 1199.19   694.9 1200.05
   702.5 1202.68   712.5 1208.07   722.6 1210.91   742.7 1212.27   752.7 1216.41
   772.8  1229.4   782.8 1232.31   893.4 1246.96   903.4 1249.75   923.5 1258.34
    1024 1308.23  1074.2 1332.13  1174.7 1396.49  1255.1 1444.65  1365.7 1517.86
#Mann= 3 , 0 , 0
      10     .06       0   669.9    .045       0   694.9     .06       0
#XS Ineff= 2 , 0
          595.71 1240.62
Permanent Ineff=
       F       F
Bank Sta=669.9,694.9
XS Rating Curve= 0 ,0
Exp/Cntr=0.3,0.1

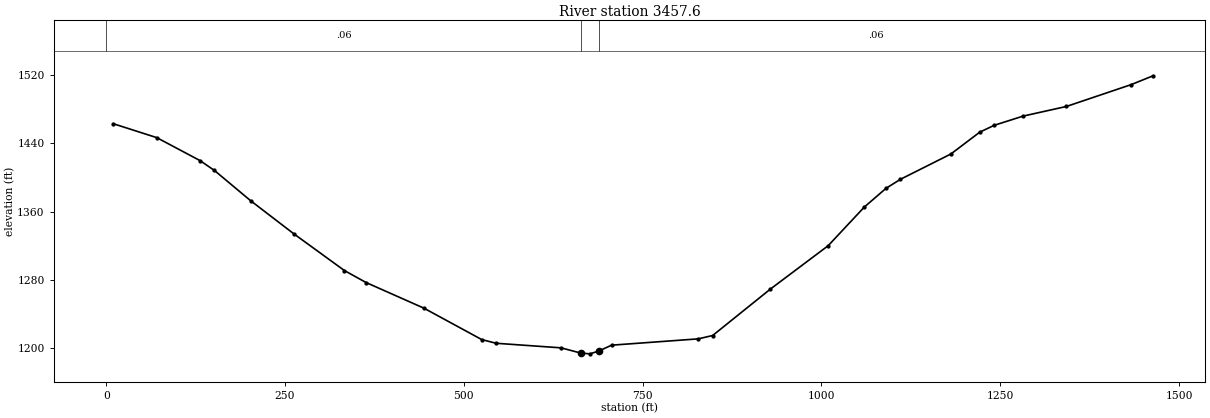
Type RM Length L Ch R = 1 ,3457.6  ,581.3,573.1,565
XS GIS Cut Line= 2
     1733537.529      127102.535     1734946.225      126704.624
#Sta/Elev= 30
    10.1 1462.92    70.7 1446.69   131.2  1419.8   151.4 1408.22   201.9 1372.88
   262.5    1334   333.1 1291.08   363.4 1277.06   444.2 1247.07     525 1210.32
   545.1 1205.96     636  1200.6   663.9 1194.41   676.4 1193.58   688.9 1196.92
   706.7 1203.72   827.8 1211.11     848 1215.04   928.8 1269.45  1009.5 1320.17
    1060 1365.37  1090.3 1387.28  1110.5 1397.88  1181.1 1427.55  1221.5 1453.12
  1241.7 1461.12  1282.1  1471.9  1342.7  1483.2  1433.5 1508.84  1463.8  1519.1
#Mann= 3 , 0 , 0
       0     .06       0   663.9    .045       0   688.9     .06       0
Bank Sta=663.9,688.9
XS Rating Curve= 0 ,0
Exp/Cntr=0.3,0.1