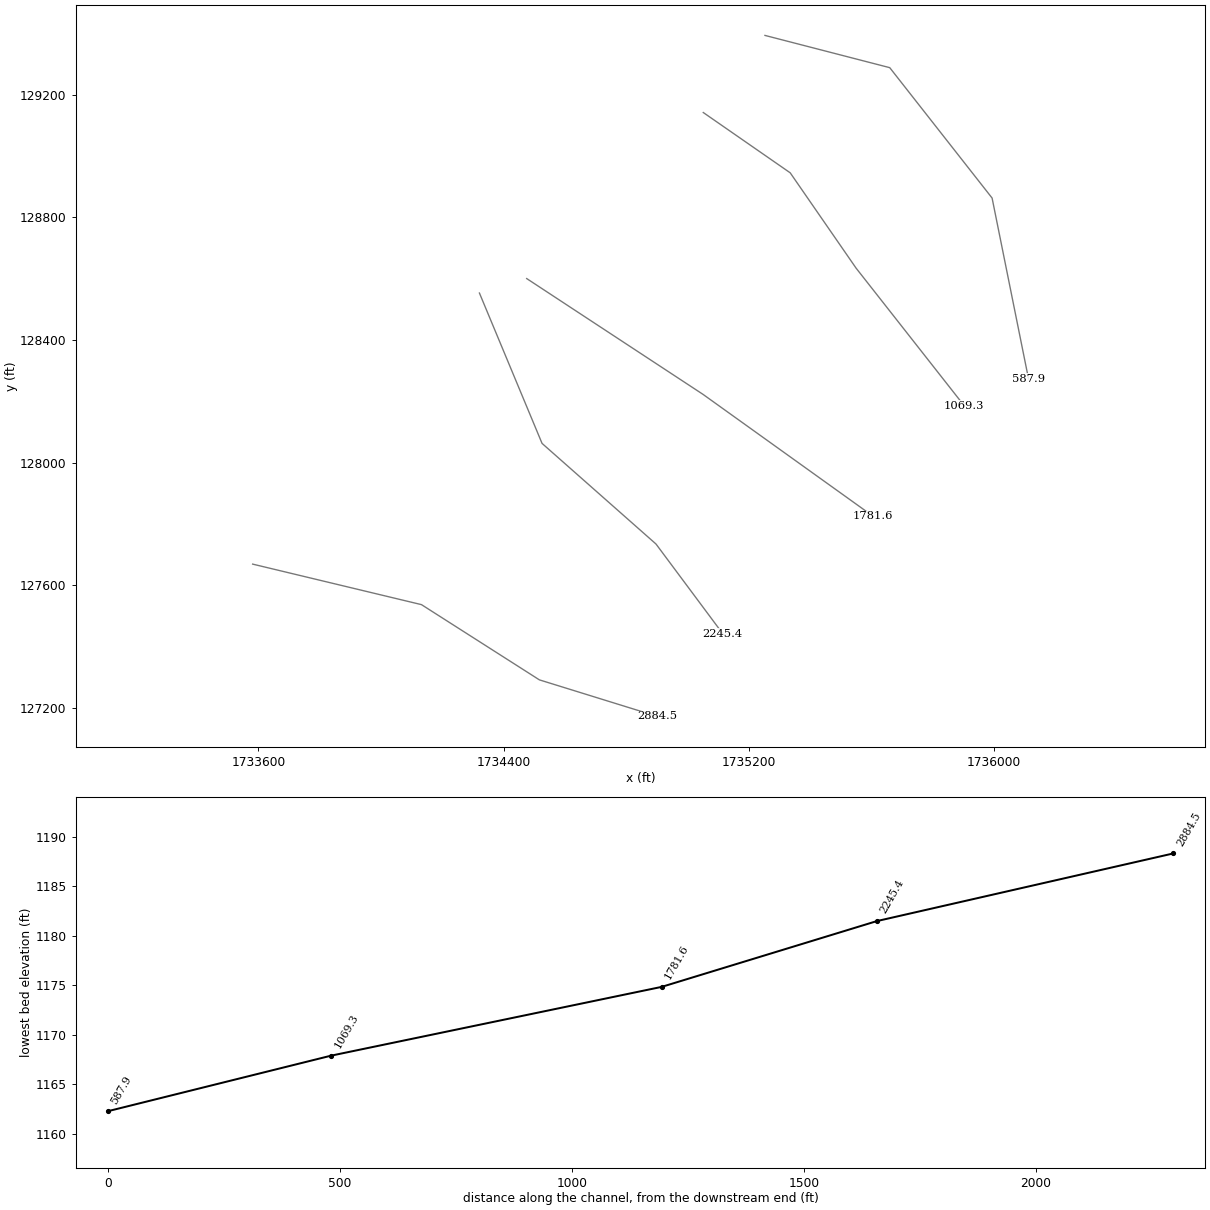
HEC-RAS study Bradshaw Creek.prj: Bradshaw Creek

--- Bradshaw Creek.g01 (geometry) --- (continued)

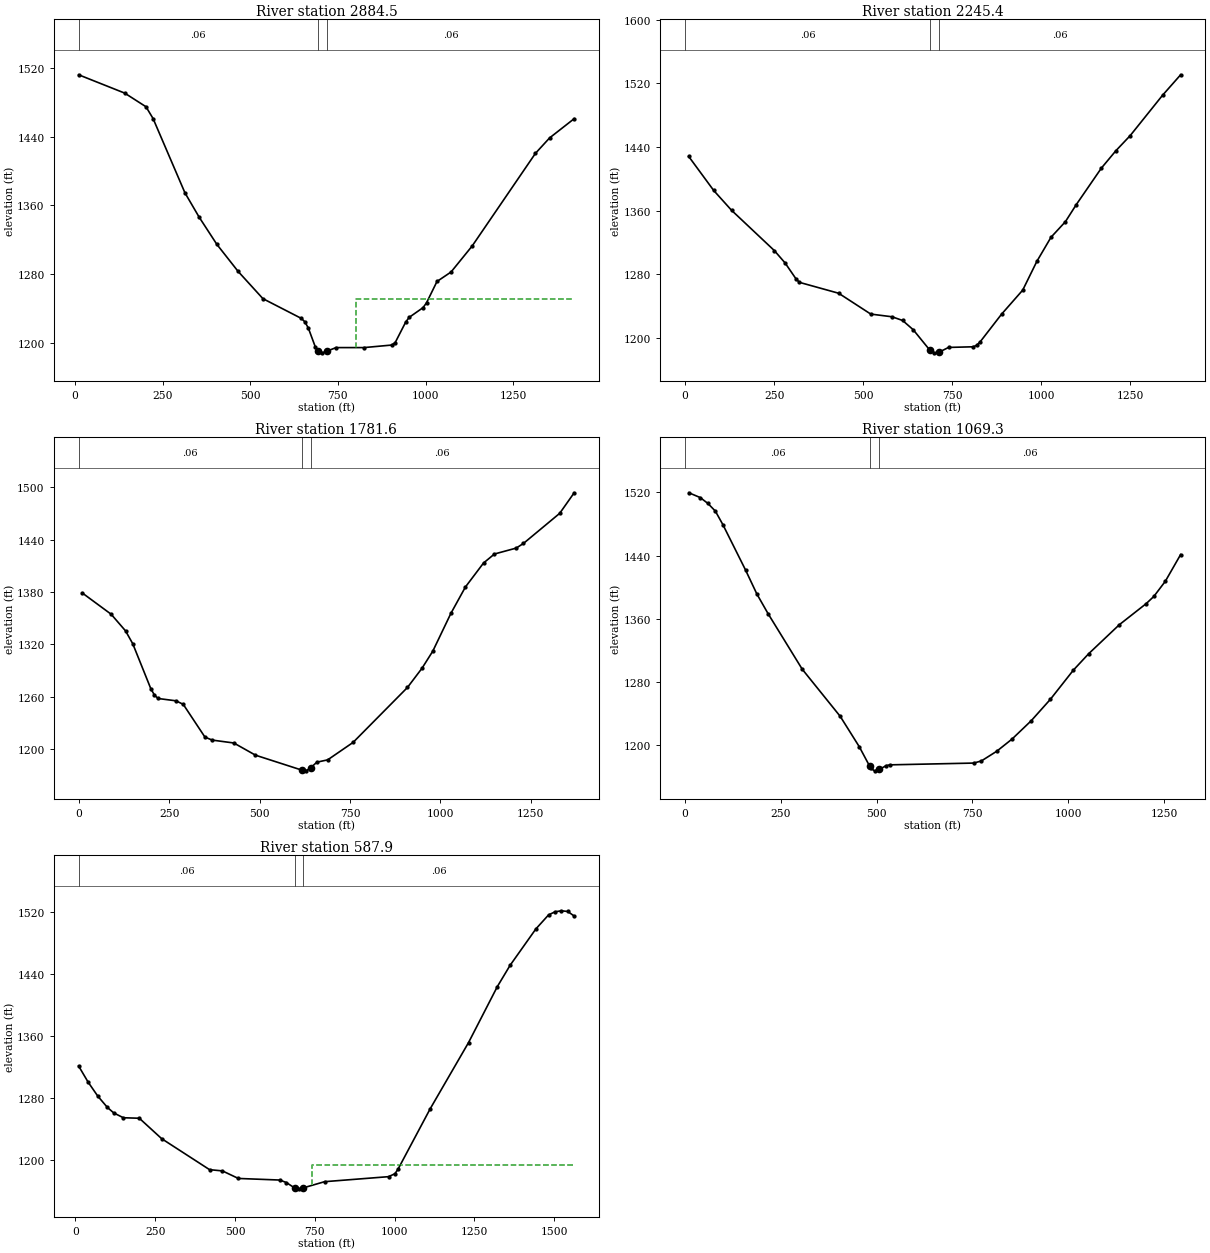
Type RM Length L Ch R = 1 ,2884.5  ,643.5,639.1,634.8
XS GIS Cut Line= 4
     1733581.392      127669.221     1734132.108      127537.035
     1734516.779      127291.606     1734900.388      127172.781
#Sta/Elev= 30
    10.1 1511.94   141.6  1490.6   202.3 1474.73   222.5 1461.02   313.5 1374.51
     354 1346.23   404.5 1314.58   465.2 1283.08     536 1251.36   645.7 1228.36
   655.6 1224.42   665.6 1217.13   685.4 1195.31   692.7 1190.53   705.2  1188.3
   717.7 1190.13   744.9 1194.41   824.3  1194.4   903.6 1197.36   913.5 1200.28
   943.3 1223.99   953.2 1229.55   992.9 1240.89  1002.8 1246.48  1032.7 1271.35
  1072.9  1282.4  1133.1 1312.66  1313.8 1420.55    1354 1438.43  1424.2 1460.83
#Mann= 3 , 0 , 0
    10.1     .06       0   692.7    .045       0   717.7     .06       0
#XS Ineff= 2 , 0
                          800.66         1250.76
Permanent Ineff=
       F       F
Bank Sta=692.7,717.7
XS Rating Curve= 0 ,0
Exp/Cntr=0.3,0.1

Type RM Length L Ch R = 1 ,2245.4  ,459.8,463.8,467.7
XS GIS Cut Line= 4
     1734321.157      128553.534     1734525.446       128063.01
     1734897.244      127734.694      1735114.63        127442.7
#Sta/Elev= 30
      10 1428.16    80.2 1385.43   130.3 1360.53   250.6 1309.87   280.7 1294.38
   310.8 1274.76   320.8 1270.01   431.1 1256.31   521.3 1230.14     581 1226.76
   610.7 1222.12   640.5  1210.5   687.5 1184.68     700 1181.47   712.5 1182.15
   739.7 1188.27   809.1 1189.07   819.1 1191.02     829 1195.59   888.5 1229.97
     948 1260.24   987.7 1296.36  1027.4  1326.6  1067.8 1346.14  1098.2 1367.49
  1168.9 1413.47  1209.4 1435.18  1249.8 1454.27  1340.8 1505.02  1391.4 1530.64
#Mann= 3 , 0 , 0
       0     .06       0   687.5    .045       0   712.5     .06       0
Bank Sta=687.5,712.5
XS Rating Curve= 0 ,0
Exp/Cntr=0.3,0.1

Type RM Length L Ch R = 1 ,1781.6  ,723,712.3,701.6
XS GIS Cut Line= 3
     1734475.368      128600.752     1735050.786       128222.82
     1735604.664      127825.916
#Sta/Elev= 30
      10 1378.77    89.8  1354.4   129.7 1335.29   149.7 1320.47   199.5 1269.04
   209.5 1261.75   219.5 1257.78   269.4  1255.1   289.3    1251   349.2 1213.49
   369.2 1210.08     429 1206.76   488.9 1192.78   616.1 1175.78   628.6 1174.83
   641.1 1178.24   658.5 1184.76   688.4 1187.41   758.6  1207.4   908.9 1270.39
     949 1292.35     979 1312.04  1029.1 1355.42  1069.2 1385.61  1119.3 1413.14
  1149.4 1423.42  1209.5  1430.2  1229.5 1435.51  1329.8 1470.05  1369.8 1493.62
#Mann= 3 , 0 , 0
       0     .06       0   616.1    .045       0   641.1     .06       0
Bank Sta=616.1,641.1
XS Rating Curve= 0 ,0
Exp/Cntr=0.3,0.1

Type RM Length L Ch R = 1 ,1069.3  ,479.6,481.4,483.1
XS GIS Cut Line= 4
      1735051.42      129142.401     1735334.989      128945.732
     1735549.952      128634.721     1735902.127      128186.499
#Sta/Elev= 30
     9.9 1519.52    39.4 1513.48    59.2 1506.17    78.9 1496.38    98.6 1479.23
   157.8  1421.8   187.3  1391.5   216.9 1366.34   305.7 1296.38   404.8  1236.8
   454.5 1198.43   481.8 1173.66   484.4  1171.3   494.3 1167.89   506.8 1169.59
   524.2 1174.35   534.1 1175.46   753.2 1177.71   773.2  1180.4   813.2 1192.63
   853.2 1208.06   903.2 1231.21   953.2 1258.29  1013.2  1295.2  1053.2 1315.99
  1133.2 1352.68  1203.2  1379.3  1223.2 1388.39  1253.2 1407.59  1293.2 1441.41
#Mann= 3 , 0 , 0
       0     .06       0   481.8    .045       0   506.8     .06       0
Bank Sta=481.8,506.8
XS Rating Curve= 0 ,0
Exp/Cntr=0.3,0.1

Type RM Length L Ch R = 1 ,587.9   ,571.8,587.9,604
XS GIS Cut Line= 4
     1735252.663      129393.954     1735659.721      129288.759
       1735993.6      128863.405     1736112.516      128273.399
#Sta/Elev= 30
      10 1320.76      40 1299.83    70.1  1281.9   100.1 1267.38   120.1 1260.23
   150.2 1254.03   200.2 1253.39   270.3 1226.99   420.4 1187.01   460.5 1185.44
   510.6 1175.69   640.7 1173.62   660.8 1170.44   688.3 1163.05   700.8 1162.28
   713.3 1163.45   780.9 1171.52   981.2 1177.99  1001.3 1181.79  1011.3 1187.91
  1111.6 1265.48    1232 1351.07  1322.3 1423.34  1362.4 1450.88  1442.7 1497.56
  1482.8 1515.84  1502.9 1519.78  1522.9 1521.13    1543 1520.22    1563 1514.34
#Mann= 3 , 0 , 0
      10     .06       0   688.3    .045       0   713.3     .06       0
#XS Ineff= 2 , 0
                          741.86         1192.93
Permanent Ineff=
       F       F
Bank Sta=688.3,713.3
XS Rating Curve= 0 ,0
Exp/Cntr=0.3,0.1

Chan Stop Cuts=-1
Use User Specified Reach Order=0